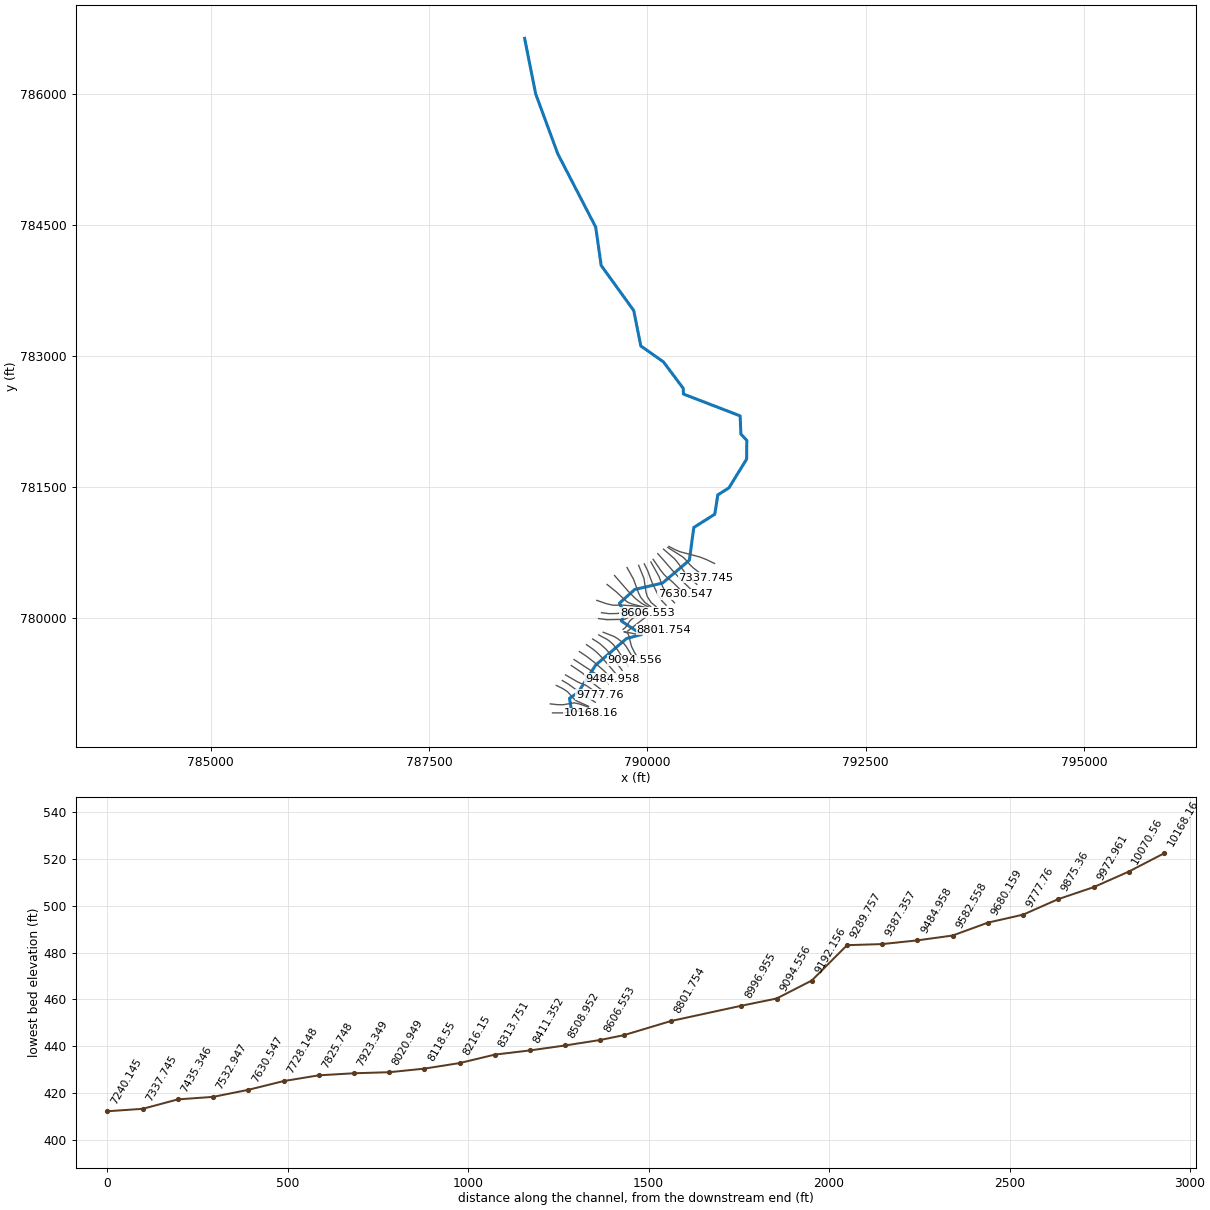
--- 17510_ras.prj (project) ---

Proj Title=17510
Current Plan=p01
Default Exp/Contr=0.3,0.1
English Units
Geom File=g01
Flow File=f01
Plan File=p01
Y Axis Title=Elevation
X Axis Title(PF)=Main Channel Distance
X Axis Title(XS)=Station
BEGIN DESCRIPTION:
RFD model 17510 exported to HEC-RAS
END DESCRIPTION:

--- 17510_ras.p01 (plan) ---

Plan Title=Plan 01
Program Version=4.10
Short Identifier=Plan 01
Geom File=g01
Flow File=f01
Subcritical Flow
Calc Critical at every XS
Secant Critical Depth

--- 17510_ras.f01 (steady flow) ---

Flow Title=Flow 01
Program Version=5.01
Number of Profiles= 6
Profile Names=10yr,25yr,50yr,100yr,100plus,500yr
River Rch & RM=17510,47,10168.16
  207.32  346.68  481.78  611.75  893.15 1577.29
River Rch & RM=17510,47,10070.56
   208.9  349.34  485.49  616.48  900.06 1587.84
River Rch & RM=17510,47,9972.961
  211.76  354.15  492.19  625.01  912.51 1606.77
River Rch & RM=17510,47, 9875.36
   214.3  358.41  498.14  632.58  923.56 1623.51
River Rch & RM=17510,47, 9777.76
  215.24     360  500.36   635.4  927.68 1629.78
River Rch & RM=17510,47,9680.159
  231.02  386.47  537.27  682.33  996.21 1732.81
River Rch & RM=17510,47,9484.958
  233.82  391.19  543.85   690.7 1008.42 1751.09
River Rch & RM=17510,47,9387.357
  234.76  392.76  546.04  693.49 1012.49 1757.17
River Rch & RM=17510,47,9289.757
  239.42  400.58  556.96  707.38 1032.77 1787.45
River Rch & RM=17510,47,9094.556
  240.35  402.15  559.14  710.15 1036.82 1793.48
River Rch & RM=17510,47,8996.955
  248.06  415.11  577.23  733.16 1070.42 1843.43
River Rch & RM=17510,47,8672.123
  251.74  421.29  585.85  744.14 1086.45 1867.22
River Rch & RM=17510,47,8606.553
  254.19   425.4   591.6  751.46 1097.13 1883.01
River Rch & RM=17510,47,8313.751
   256.3  428.97  596.58  757.81  1106.4 1896.79
River Rch & RM=17510,47, 8216.15
   257.8   431.5  600.13  762.33 1113.01  1906.6
River Rch & RM=17510,47, 8118.55
   259.3  434.03  603.67  766.85  1119.6  1916.4
River Rch & RM=17510,47,8020.949
  260.79  436.56  607.21  771.36 1126.19 1926.18
River Rch & RM=17510,47,7825.748
  264.08  442.11  614.98  781.28 1140.67 1947.62
River Rch & RM=17510,47,7728.148
  267.37  447.65  622.74  791.17 1155.11 1968.97
River Rch & RM=17510,47,7532.947
  271.83  455.19  633.28  804.62 1174.75 1997.93
River Rch & RM=17510,47,7435.346
   275.1  460.69  640.99  814.45  1189.1 2019.07
River Rch & RM=17510,47,7240.145
  276.57  463.19  644.48  818.91 1195.61 2028.65
River Rch & RM=17510,47,7142.544
  278.08  465.72  648.02  823.41 1202.17 2038.21
River Rch & RM=17510,47,7044.944
   282.5  473.18  658.46  836.74 1221.63 2066.79
River Rch & RM=17510,47,6947.343
  285.73  478.64   666.1  846.48 1235.87 2087.65
River Rch & RM=17510,47,6849.743
  287.19  481.11  669.57  850.91 1242.32  2097.1
River Rch & RM=17510,47,6752.142
  290.15   486.1  676.54  859.78 1255.28 2115.96
River Rch & RM=17510,47,6556.941
  293.79  492.18     685  870.52 1270.96 2138.51
River Rch & RM=17510,47, 6459.34
  294.99  494.19   687.8  874.08 1276.16    2146
River Rch & RM=17510,47, 6361.74
  295.89  495.71  689.91  876.76 1280.07 2151.61
River Rch & RM=17510,47,6264.139
  300.67  503.72  701.09  890.96  1300.8 2181.46
River Rch & RM=17510,47,6166.539
  385.18  645.51  898.84 1142.28 1667.73 2699.66
River Rch & RM=17510,47,5972.018
  386.05  646.98  900.87 1144.85 1671.48 2704.79
River Rch & RM=17510,47,5730.444
  388.69  651.36  906.95 1152.54 1682.71 2720.16
River Rch & RM=17510,47, 5488.87
  390.15  653.79  910.32 1156.81 1688.94 2728.69
River Rch & RM=17510,47,5247.296
  390.74  654.77  911.67 1158.51 1691.43 2732.09
Boundary for River Rch & Prof#=17510,47,1
Up Type= 0
Dn Type= 2
Boundary for River Rch & Prof#=17510,47,2
Up Type= 0
Dn Type= 2
Boundary for River Rch & Prof#=17510,47,2
Up Type= 0
Dn Type= 2
Boundary for River Rch & Prof#=17510,47,2
Up Type= 0
Dn Type= 2
Boundary for River Rch & Prof#=17510,47,2
Up Type= 0
Dn Type= 2
Boundary for River Rch & Prof#=17510,47,2
Up Type= 0
Dn Type= 2

--- 17510_ras.g01 (geometry) ---

Geom Title=17510
Program Version=4.10

River Reach=17510,47
Reach XY= 30
789134.839599939 778925.12082544789109.935064436779079.520399946
789210.015412839779149.604889475789409.130417764779460.531559013
789763.129138677779765.274504325789935.896645605 779811.78883313
789704.640175107779964.758337443789737.673501404780058.558793645
789681.198478728780169.518518044789856.237417134780326.433297818
790175.777684034780400.527337511790482.890407804780662.450759274
790533.321087927781036.746724959790773.887955698781189.048054491
790808.146931678781409.508260285790935.811810194781490.774147991
791138.144896508781819.113740679791140.277559579782035.155623486
791072.577178658782105.587735154791064.295564055782314.747454485
790414.818653049782564.635430148 790412.56575355782630.278306065
790185.036292582782933.794030394789926.537403048783115.416680155
789845.259506556783521.530018468789472.715855303784037.313795136
789410.261633965784476.009828046788975.684044301785315.766653868
788722.678688466 786002.40023724788596.002705247786638.622206293

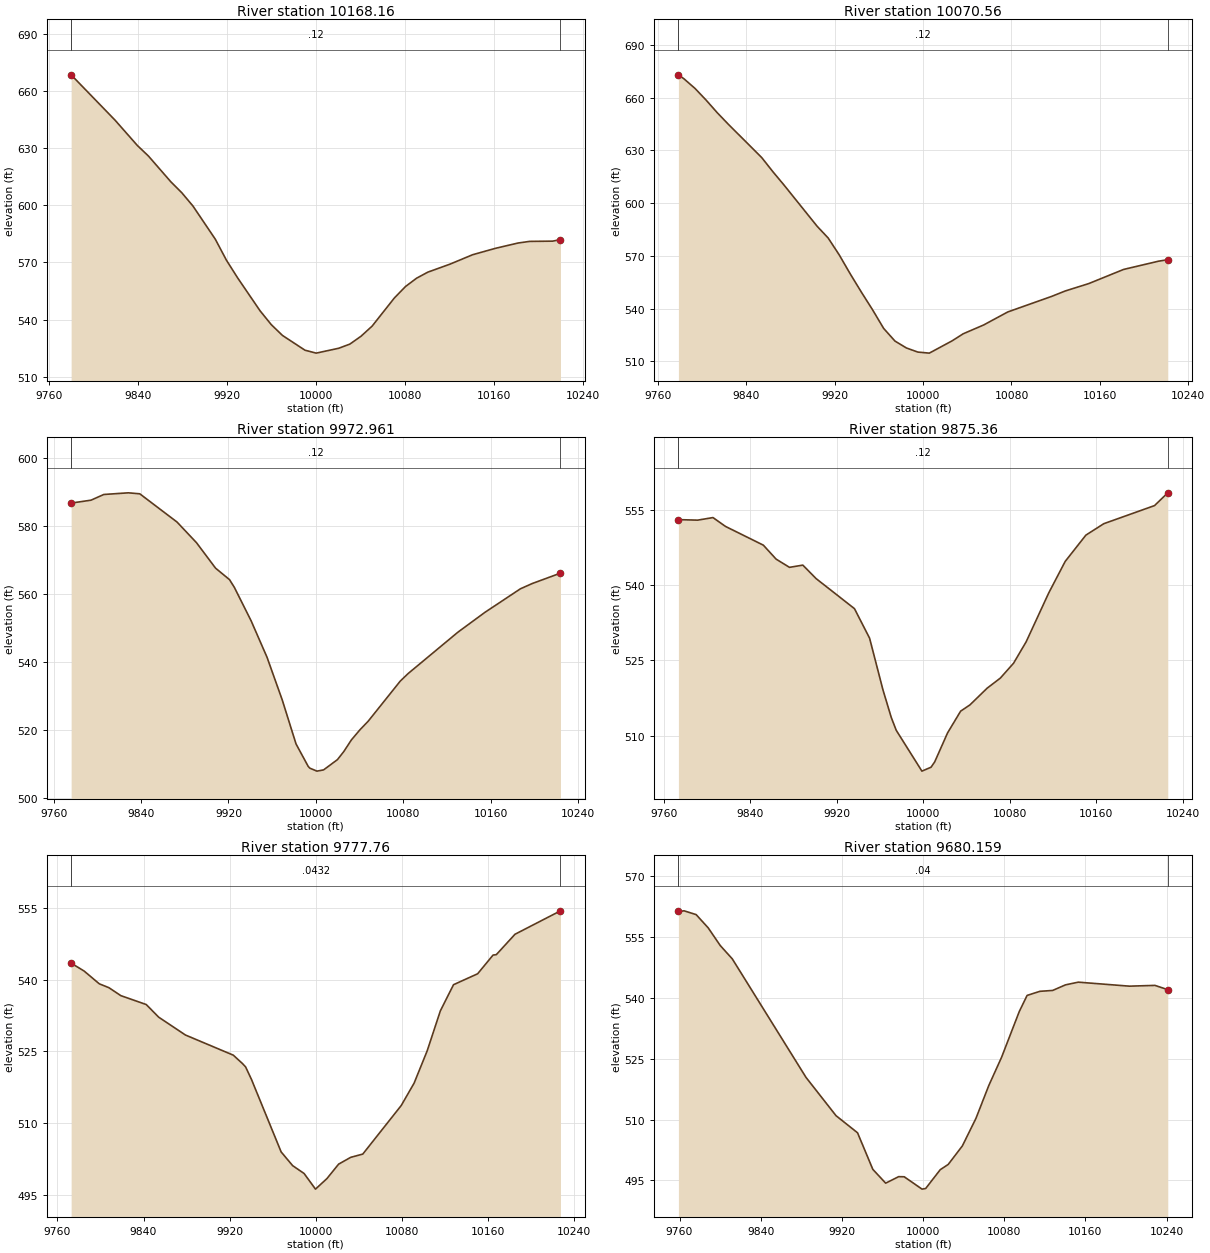
Type RM Length L Ch R = 1 ,10168.16,97.600600,97.600600,97.600600
XS GIS Cut Line= 6
788915.454751501778913.303414849789031.672891999778913.249031458
789165.825217947778930.365669601789214.271237478778932.586976652
789274.856217414778926.650351875789351.771268969778907.846484212
#Sta/Elev= 30
 9779.89668.39489819.456644.57729839.466 631.3349849.471 625.7769869.482612.3617
9879.487606.51989889.492599.5668 9909.56582.20379919.608571.15759929.656561.9051
 9949.78544.6887 9959.89537.39319969.999531.70959990.218 523.97110000.33522.4324
10020.52524.976410030.61527.160210040.63 531.27810050.64536.598610070.66551.3667
10080.67557.360210090.68561.7508 10100.7564.891410120.83569.130910141.01574.0303
10161.47577.381610181.94 580.18110192.25581.033410213.04581.160510220.08581.9865
#Mann= 3 , 0 , 0
 9779.89    0.12       0 9779.89    0.12       010220.08    0.12       0
#XS Ineff= 2 , 0
       0                               0
Bank Sta=9779.89,10220.08
Exp/Cntr=0.3,0.1

Type RM Length L Ch R = 1 ,10070.56,97.600500,97.600500,97.600500
XS GIS Cut Line= 6
788889.978447038779016.461865702788969.909269877779007.729126226
789035.924829915779006.634518706789163.452714997779028.274418508
789223.583055949779015.178903223789322.666882019778980.602817176
#Sta/Elev= 30
9778.546672.94289783.598670.67299793.657665.15849803.717658.49719813.776651.3376
9823.836644.75999854.014625.82699864.044617.83589874.046610.3166 9904.05586.8413
9914.051580.15839924.053 570.5729934.116559.66289944.185549.30249954.254539.3065
9964.324528.6923 9974.54521.5094 9984.89517.58319995.241515.246710005.61514.6482
 10026.3521.652310036.38525.675710054.85530.674510076.64 538.06810116.48546.9503
10128.58549.988210149.76554.169110181.53562.263410213.31566.969310221.43567.7764
#Mann= 3 , 0 , 0
9778.546    0.12       09778.546    0.12       010221.43    0.12       0
#XS Ineff= 2 , 0
       0                               0
Bank Sta=9778.546,10221.43
Exp/Cntr=0.3,0.1

Type RM Length L Ch R = 1 ,9972.961,97.600600,97.600600,97.600600
XS GIS Cut Line= 6
788958.737215341779228.337967435789033.575957076779191.072194281
 789087.97330576779155.467735292789160.475141619779073.471301862
789185.087101499779053.485904914789328.908482446778988.854197676
#Sta/Elev= 30
9775.954  586.879794.121587.72019805.877589.39959828.311589.88729838.806589.5996
9872.895581.29019890.696575.22169908.158567.7221 9920.97 564.3369925.337562.0876
9940.739552.2215 9955.29541.5005 9969.21 528.956 9981.85515.98979992.976509.3844
9994.489508.8598   10001507.984210007.07 508.34510019.79511.376910025.59513.7486
10032.51517.160910040.28520.118110047.89522.665410077.34534.505910084.48 536.702
10129.97 548.85410154.73 554.69810187.23561.634110198.06563.190610223.96566.2547
#Mann= 3 , 0 , 0
9775.954    0.12       09775.954    0.12       010223.96    0.12       0
#XS Ineff= 2 , 0
       0                               0
Bank Sta=9775.954,10223.96
Exp/Cntr=0.3,0.1

Type RM Length L Ch R = 1 , 9875.36,97.600600,97.600600,97.600600
XS GIS Cut Line= 6
789027.557268267779284.120558423789102.501294729779239.334279041
 789193.89148066779173.095029488789237.914285249779144.956903186
789311.610323149779092.945838028 789405.43011405779035.383859911
#Sta/Elev= 30
9773.665553.07799791.444552.97299805.634 553.4879817.284551.71619852.233547.9864
9864.057545.19619876.408 543.5589888.758544.00029901.109541.30179936.516535.3219
 9950.51529.43299962.861519.13529970.596513.59629975.159511.05349998.925502.9016
 10007.4503.687510010.78504.755610022.63510.515110034.76514.869310043.36516.1158
10059.24519.445110071.48 521.46210083.72 524.43410095.39 528.71510116.29538.4691
10131.48544.741610150.61549.9834 10167.2552.267210214.12555.877210226.36558.4246
#Mann= 3 , 0 , 0
9773.665    0.12       09773.665    0.12       010226.36    0.12       0
#XS Ineff= 2 , 0
       0                               0
Bank Sta=9773.665,10226.36
Exp/Cntr=0.3,0.1

Type RM Length L Ch R = 1 , 9777.76,97.600500,97.600500,97.600500
XS GIS Cut Line= 6
 789064.60471676779348.093445184789202.245093714779268.570338316
789235.797494709779253.196696509789282.172856251779236.343177683
789306.368975165779224.091892511789456.143760705779120.638293826
#Sta/Elev= 30
9772.804543.43939784.809541.80679798.977539.12669807.907538.31739818.966536.6601
9842.554534.80249854.104532.16519878.934528.43869923.398524.22829931.765522.5052
9934.796521.78469940.336519.12439967.795504.03079978.459501.16289989.093499.5236
9999.713496.252710010.36498.461210021.19501.4718 10032.4502.891110043.61503.5692
10079.32513.715410091.26  518.3810103.39525.114110115.63533.463110127.87538.9436
10150.28541.228510164.59545.132810167.62545.222910184.96549.4781 10227.2554.3722
#Mann= 3 , 0 , 0
9772.804  0.0432       09772.804  0.0432       0 10227.2  0.0432       0
#XS Ineff= 2 , 0
       0                               0
Bank Sta=9772.804,10227.2
Exp/Cntr=0.3,0.1

Type RM Length L Ch R = 1 ,9680.159,97.600600,97.600600,97.600600
XS GIS Cut Line= 6
789130.279425384779456.216147439 789258.81942063779369.162123503
789285.784981583 779344.90916888789314.490431511779308.744813412
789351.099699773779273.946259658789505.006490239779155.993182769
#Sta/Elev= 30
9758.923561.35379764.529561.50929776.404 560.5759788.279557.30679800.154 552.942
9812.028549.64999884.716520.38849914.242 510.963 9935.42506.74719950.509 497.721
9963.161494.31239975.928495.91619981.416495.8889    9999492.841110002.56492.9948
10016.95497.640610024.82498.939310038.74503.508510052.14510.312310064.74518.3818
10077.34525.353310094.81536.659210102.53540.637710115.13541.647610127.73541.8648
10140.33543.239710152.93543.908110203.33542.920110228.52543.110410241.13542.0613
#Mann= 3 , 0 , 0
9758.923    0.04       09758.923    0.04       010241.13    0.04       0
#XS Ineff= 2 , 0
       0                               0
Bank Sta=9758.923,10241.13
Exp/Cntr=0.3,0.1

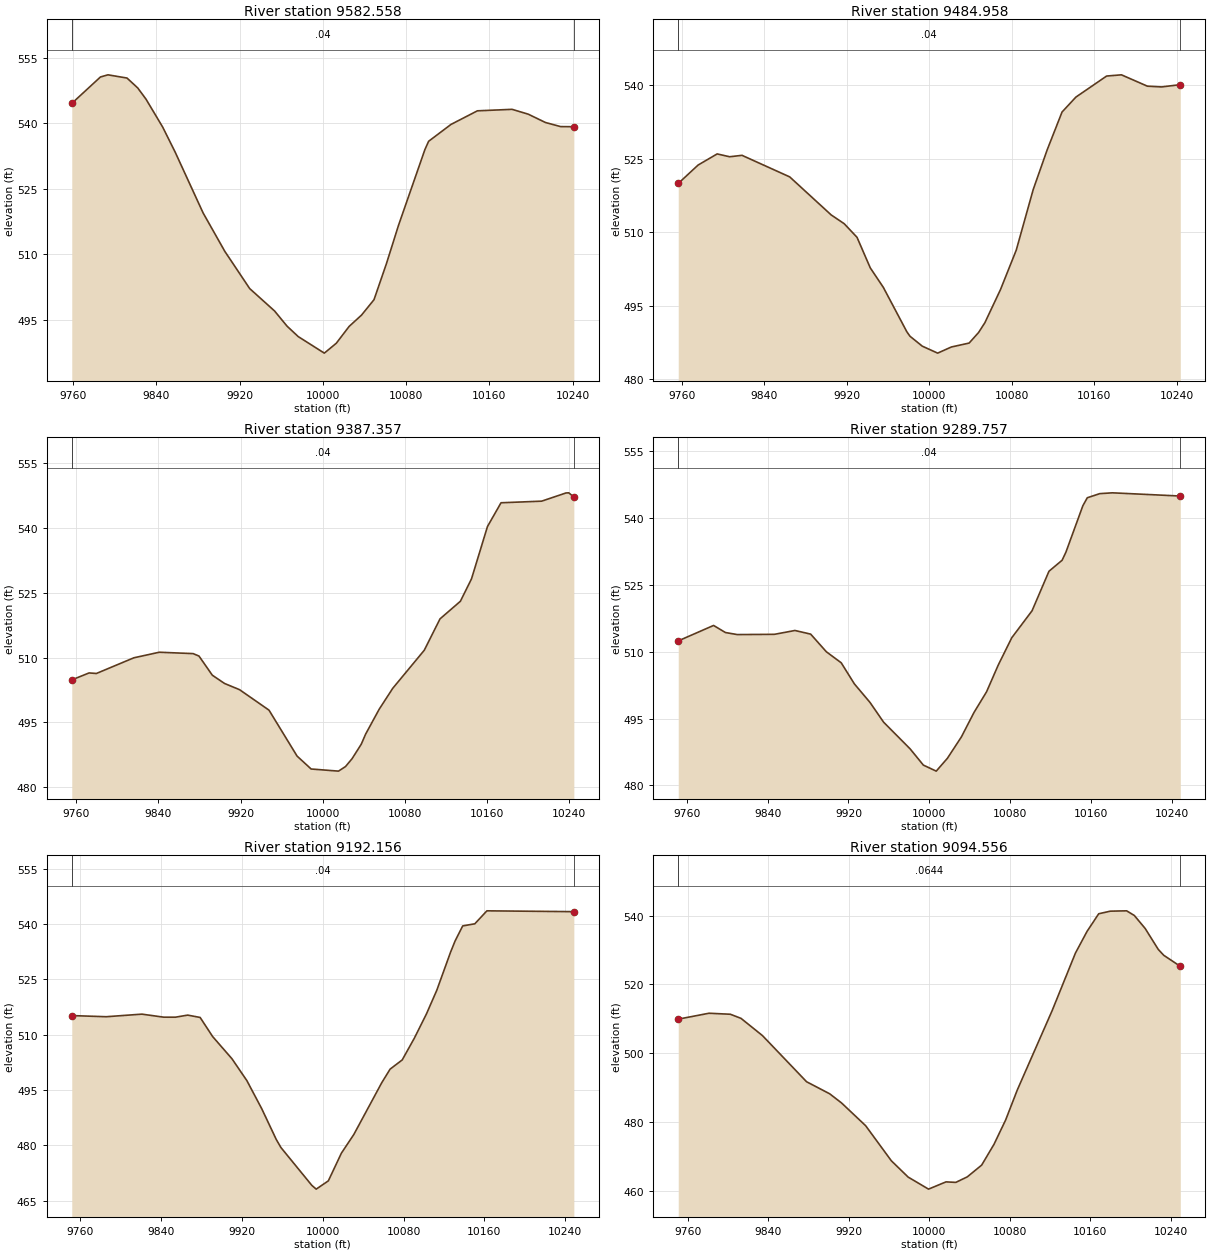
Type RM Length L Ch R = 1 ,9582.558,97.600600,97.600600,97.600600
XS GIS Cut Line= 6
789161.933026616779524.042565716789362.937538066779392.610481448
789364.603109661 779391.50329074789424.717702958779352.397347856
789478.365498903779312.059795258789555.860103449779246.784744564
#Sta/Elev= 30
9758.839 544.564  9786.4550.62399793.635 551.1169811.908550.37729822.244548.0999
 9830.18545.5288 9846.14539.15779858.088 533.4429884.998519.4678 9905.88510.6544
9929.776502.12479953.672 496.992 9965.62493.52319976.361491.127210001.47487.3327
10012.93489.592510025.33493.462310037.26496.065110049.19499.579710061.12507.8372
10072.71516.608110098.09533.993310101.66535.886910123.11539.742110148.51542.8656
10181.84543.206310197.36 542.09710213.88540.190710228.41539.250810241.16539.2226
#Mann= 3 , 0 , 0
9758.839    0.04       09758.839    0.04       010241.16    0.04       0
#XS Ineff= 2 , 0
       0                               0
Bank Sta=9758.839,10241.16
Exp/Cntr=0.3,0.1

Type RM Length L Ch R = 1 ,9484.958,97.600500,97.600500,97.600500
XS GIS Cut Line= 6
789223.681377877779615.757588574789309.106033944779558.159801054
789397.592885118779489.633981431789419.603200011779469.740582469
789498.827209379779400.881083209789597.970560391779305.377035753
#Sta/Elev= 30
9756.383519.95779775.626523.71789794.156525.99989806.216525.41969818.277525.7102
9864.572521.3021 9904.81513.52819917.458 511.7319929.901508.94759942.754502.7012
9955.402498.72589978.265489.63069981.286488.72369993.229486.696410008.15485.2733
 10021.4486.524310038.71487.3315 10047.9489.500610053.96491.4887 10069.2498.2988
10084.44506.3453 10100.9518.734210114.44526.834210128.86534.564910142.31537.6172
 10172.1541.918510186.51542.169210211.73 539.84610225.62539.695410243.63540.1608
#Mann= 3 , 0 , 0
9756.383    0.04       09756.383    0.04       010243.63    0.04       0
#XS Ineff= 2 , 0
       0                               0
Bank Sta=9756.383,10243.63
Exp/Cntr=0.3,0.1

Type RM Length L Ch R = 1 ,9387.357,97.600600,97.600600,97.600600
XS GIS Cut Line= 6
789304.984683734779694.266407617789379.932443875779642.089431277
 789416.48526448 779611.82952065789449.519436734779580.796664315
789487.449305749779540.165344313789649.987992755779351.241960072
#Sta/Elev= 30
9755.549504.82449772.415506.44379779.503506.31249816.009509.94829840.787511.2381
9873.698510.92059879.441510.35339892.423505.91449904.326503.99839918.931 502.562
9947.605497.81819974.966487.16579988.646484.175310015.28483.681910022.15 484.746
10028.47 486.54910037.48489.926910041.66492.233310054.86498.004910068.15 502.884
10098.82511.698310114.15518.9683   10134523.051910144.82528.246210160.38540.3794
10173.57545.881710213.14 546.25310236.83548.155210239.52548.185710244.48547.2173
#Mann= 3 , 0 , 0
9755.549    0.04       09755.549    0.04       010244.48    0.04       0
#XS Ineff= 2 , 0
       0                               0
Bank Sta=9755.549,10244.48
Exp/Cntr=0.3,0.1

Type RM Length L Ch R = 1 ,9289.757,97.600600,97.600600,97.600600
XS GIS Cut Line= 6
789375.174412173779759.157026687789428.113073562779726.687897523
789465.089640325779700.101701476  789528.6850107779642.384995999
789565.722770477779598.592595557789712.589402833779401.095805386
#Sta/Elev= 30
9751.491512.4141 9786.48 515.8799798.211 514.2929809.942513.83089846.709513.8881
9867.064514.75039882.604513.93379898.144509.97249912.841507.50759925.883502.7733
9941.355498.61639954.826494.18819981.045488.21019994.177484.562710006.92483.2138
10017.99486.095910031.84490.891110044.31496.366910056.77501.011310068.26506.9733
10081.69513.118410101.78519.169910118.54528.033310131.54530.4987 10135.3 532.305
10152.05542.705710156.46544.511110168.81545.433310181.39545.616310248.56544.8958
#Mann= 3 , 0 , 0
9751.491    0.04       09751.491    0.04       010248.56    0.04       0
#XS Ineff= 2 , 0
       0                               0
Bank Sta=9751.491,10248.56
Exp/Cntr=0.3,0.1

Type RM Length L Ch R = 1 ,9192.156,97.600500,97.600500,97.600500
XS GIS Cut Line= 6
789444.423107281779806.280392173789539.270851605779755.523398542
789575.146434667779729.483756438789609.342498544779697.984292793
789658.644319982779636.717671053789780.934827795779453.991757546
#Sta/Elev= 30
9751.506515.16059785.643  514.859820.909515.54999842.569514.72879854.189514.7254
9866.231515.28769878.587514.65539890.944509.48389910.099503.45359924.859497.5257
9939.619489.88719953.941481.57829958.562479.39049989.105469.14789993.488468.1063
10005.52470.348510018.43477.852510030.74482.921510058.39496.960610066.67500.6447
10078.65503.138910090.63509.020110102.61515.591510112.89522.033610126.56532.3923
10131.05535.422910138.54539.474410150.52540.0473 10162.5 543.56410248.56543.3367
#Mann= 3 , 0 , 0
9751.506    0.04       09751.506    0.04       010248.56    0.04       0
#XS Ineff= 2 , 0
       0                               0
Bank Sta=9751.506,10248.56
Exp/Cntr=0.3,0.1

Type RM Length L Ch R = 1 ,9094.556,97.600600,97.600600,97.600600
XS GIS Cut Line= 6
789496.238604102 779836.85024195789619.842510565779788.715476151
789657.329194131 779766.06138605789728.633270057779712.148941898
789758.406848741779674.919607513789853.923075882779516.627173313
#Sta/Elev= 30
9750.683509.85689781.214511.57599802.445511.2842 9813.06510.0814 9834.37505.0644
9878.121491.65549901.128 488.1379912.812485.49699936.801478.86589962.356 468.647
 9979.04463.9107 9999.26460.409810016.62462.520110026.39462.371310037.76463.9772
10052.05467.4035 10064.3473.454110075.85480.523210087.41489.243610122.07512.3658
10145.17529.081610156.72535.399910168.28540.512910179.83 541.27110196.02541.3693
10203.64540.018710214.45536.223210227.45530.137310232.88528.436110249.32525.2213
#Mann= 3 , 0 , 0
9750.683  0.0644       09750.683  0.0644       010249.32  0.0644       0
#XS Ineff= 2 , 0
       0                               0
Bank Sta=9750.683,10249.32
Exp/Cntr=0.3,0.1

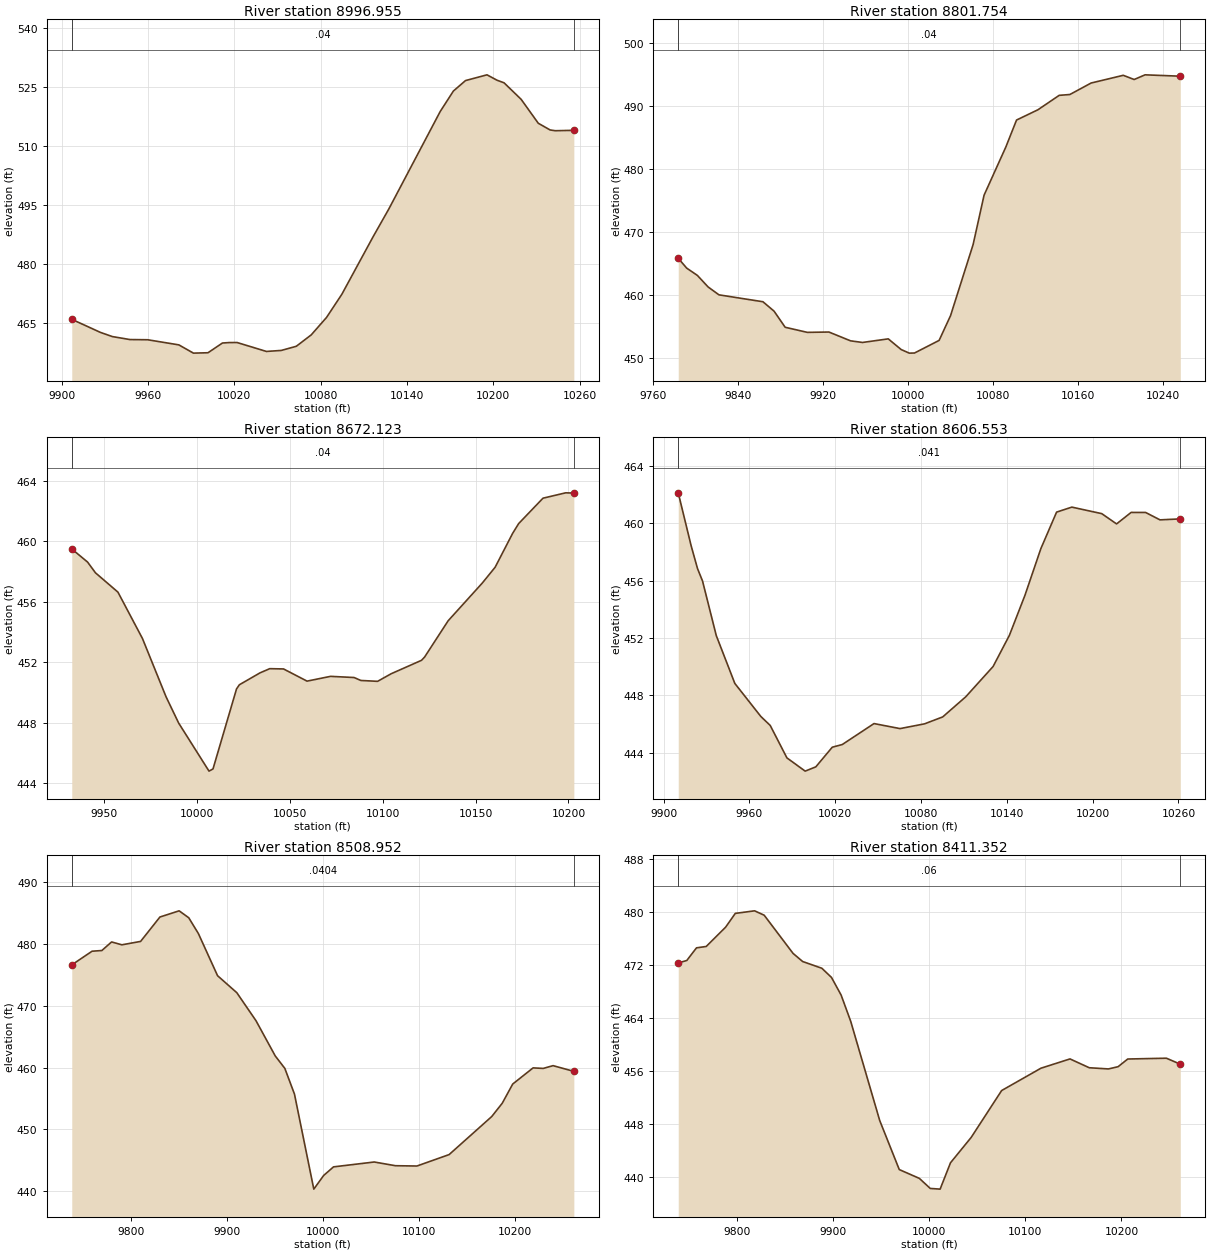
Type RM Length L Ch R = 1 ,8996.955,195.201100,195.201100,195.201100
XS GIS Cut Line= 6
789738.217631102779839.956403479 789769.10927093779829.306260437
789784.205782443779813.015544385789820.079246491779674.600275964
789853.240288377 779607.56271863789893.919378906779544.197005808
#Sta/Elev= 30
9907.093465.93799927.132462.59039935.349461.54089947.574460.78429959.876460.7342
9981.525459.42939991.662457.330610001.77457.425810011.84459.907810016.61460.0168
10021.98460.0335 10042.4457.759910052.72 458.01510063.13 459.06910073.53461.9752
10084.18466.419910094.84472.331510116.46486.907710127.42493.998210163.18518.8404
10172.34524.050210180.76 526.71310195.69528.178510202.53 526.83210207.57526.1386
10219.46521.929310231.34515.850210239.55514.144610243.22513.949210256.06514.0496
#Mann= 3 , 0 , 0
9907.093    0.04       09907.093    0.04       010256.06    0.04       0
#XS Ineff= 2 , 0
       0                               0
Bank Sta=9907.093,10256.06
Exp/Cntr=0.3,0.1

Type RM Length L Ch R = 1 ,8801.754,129.631000,129.631000,129.631000
XS GIS Cut Line= 6
789737.097079784779843.995396465 789883.42357558779813.027394697
789965.408538371779861.022218734790019.570646644779877.900378764
 790100.14783147779881.443317607790187.314833969779865.121146023
#Sta/Elev= 30
9783.617465.85689791.572464.29529801.652463.13349811.732461.30269821.917460.0519
9863.305458.95659873.768457.46379884.231454.90269905.113454.09489925.372454.1476
9945.777452.74929956.948452.49169981.206 453.0639993.406 451.363   10001450.7995
10005.91450.817110029.05452.817410039.82456.750510061.04 468.02910071.35 475.868
10091.83483.517110101.89487.797110122.01489.429310142.04491.720110152.04491.8507
10172.08493.676410202.32494.901210212.57494.233710222.83494.977610255.98494.7599
#Mann= 3 , 0 , 0
9783.617    0.04       09783.617    0.04       010255.98    0.04       0
#XS Ineff= 2 , 0
       0                               0
Bank Sta=9783.617,10255.98
Exp/Cntr=0.3,0.1

Type RM Length L Ch R = 1 ,8672.123,65.570200,65.570200,65.570200
XS GIS Cut Line= 2
789774.926779419779849.795198947789988.468446106 780015.15978229
#Sta/Elev= 30
9932.791459.49449941.292458.62769945.531457.91619957.624 456.6379970.827 453.564
9983.475449.7179 9990.29447.968710006.62444.786110008.77444.932210021.42450.2264
10022.95450.503410034.07 451.29210039.29451.568910046.71451.551410059.36450.7445
10072.01451.060810084.66450.982910088.29450.788410097.31450.730810104.62451.2337
10120.95452.1227 10122.6452.339110135.25454.737310153.62457.236110160.54458.2852
10169.95460.525510173.19461.173610186.28462.855710198.49463.210910202.88463.1955
#Mann= 3 , 0 , 0
9932.791    0.04       09932.791    0.04       010202.88    0.04       0
#XS Ineff= 2 , 0
       0                               0
Bank Sta=9932.791,10202.88
Exp/Cntr=0.3,0.1

Type RM Length L Ch R = 1 ,8606.553,97.600600,97.600600,97.600600
XS GIS Cut Line= 6
789723.410640389779870.354464933 789751.02965951779891.259855062
789802.175167829779967.903235391789845.006511658780006.571061373
789918.905584931780045.994857281789999.141353875780062.415599152
#Sta/Elev= 30
9910.249462.14019919.309458.43239923.748456.84919927.251455.98389936.828452.1841
9949.809448.84079967.966446.53669974.572 445.9059986.243443.6427    9999442.7175
10006.46443.016410017.96 444.38710024.95444.573610047.15446.036410065.35445.6851
10082.48446.017410095.19 446.50110111.27447.902910130.42 450.01910141.83452.1977
10152.66454.979910163.82 458.24610174.82460.793810185.48461.142510206.39 460.688
10216.76459.970810226.95460.773310237.08460.768610247.12460.253710261.33460.3203
#Mann= 3 , 0 , 0
9910.249   0.041       09910.249   0.041       010261.33   0.041       0
#XS Ineff= 2 , 0
       0                               0
Bank Sta=9910.249,10261.33
Exp/Cntr=0.3,0.1

Type RM Length L Ch R = 1 ,8508.952,97.600500,97.600500,97.600500
XS GIS Cut Line= 6
789444.158805365779993.674678686789538.489415161779980.689210463
789673.554380317779983.397735989789722.001049281779976.977368623
789882.941895397780051.203128838789946.029210138780069.615067806
#Sta/Elev= 30
9738.599476.56979759.758478.7806 9769.91478.88999780.063480.27589790.786479.8134
9810.275480.36239830.376484.30059850.396485.30119860.398484.1813  9870.4481.6414
9890.409474.82339910.426472.08379930.444467.55129950.462  461.87 9960.47459.8516
9970.483455.70249990.608440.361710000.86442.565310011.14443.955810053.54444.7407
10075.64444.142610097.98444.0935 10131.5445.939410175.87452.081710186.83454.2346
10197.73457.332510218.95459.940410229.46459.853410239.74460.299910261.36459.3767
#Mann= 3 , 0 , 0
9738.599  0.0404       09738.599  0.0404       010261.36  0.0404       0
#XS Ineff= 2 , 0
       0                               0
Bank Sta=9738.599,10261.36
Exp/Cntr=0.3,0.1

Type RM Length L Ch R = 1 ,8411.352,97.600600,97.600600,97.600600
XS GIS Cut Line= 6
789476.208110081780060.607675541789564.156770879 780049.77351433
789651.144616703780051.305364379789714.334639017780060.457926234
 789853.11447288780104.868953234789989.401105153780101.972422015
#Sta/Elev= 30
9738.631472.36299747.525472.72569757.642474.63599767.758474.8413 9787.99477.7581
9798.039479.83329818.108480.2191 9828.14479.55499858.145473.80279868.149472.5729
9888.172471.55529898.184470.17179908.195467.51919918.225463.53949948.403448.5829
 9968.74441.18979989.648439.8614   10001438.342910011.28 438.23910022.07442.2095
10043.64446.0463 10075.3453.106810116.28456.481310146.49457.878810166.57456.5481
10186.57456.369510196.57456.708610206.61457.865710246.84457.986810261.33457.0838
#Mann= 3 , 0 , 0
9738.631    0.06       09738.631    0.06       010261.33    0.06       0
#XS Ineff= 2 , 0
       0                               0
Bank Sta=9738.631,10261.33
Exp/Cntr=0.3,0.1

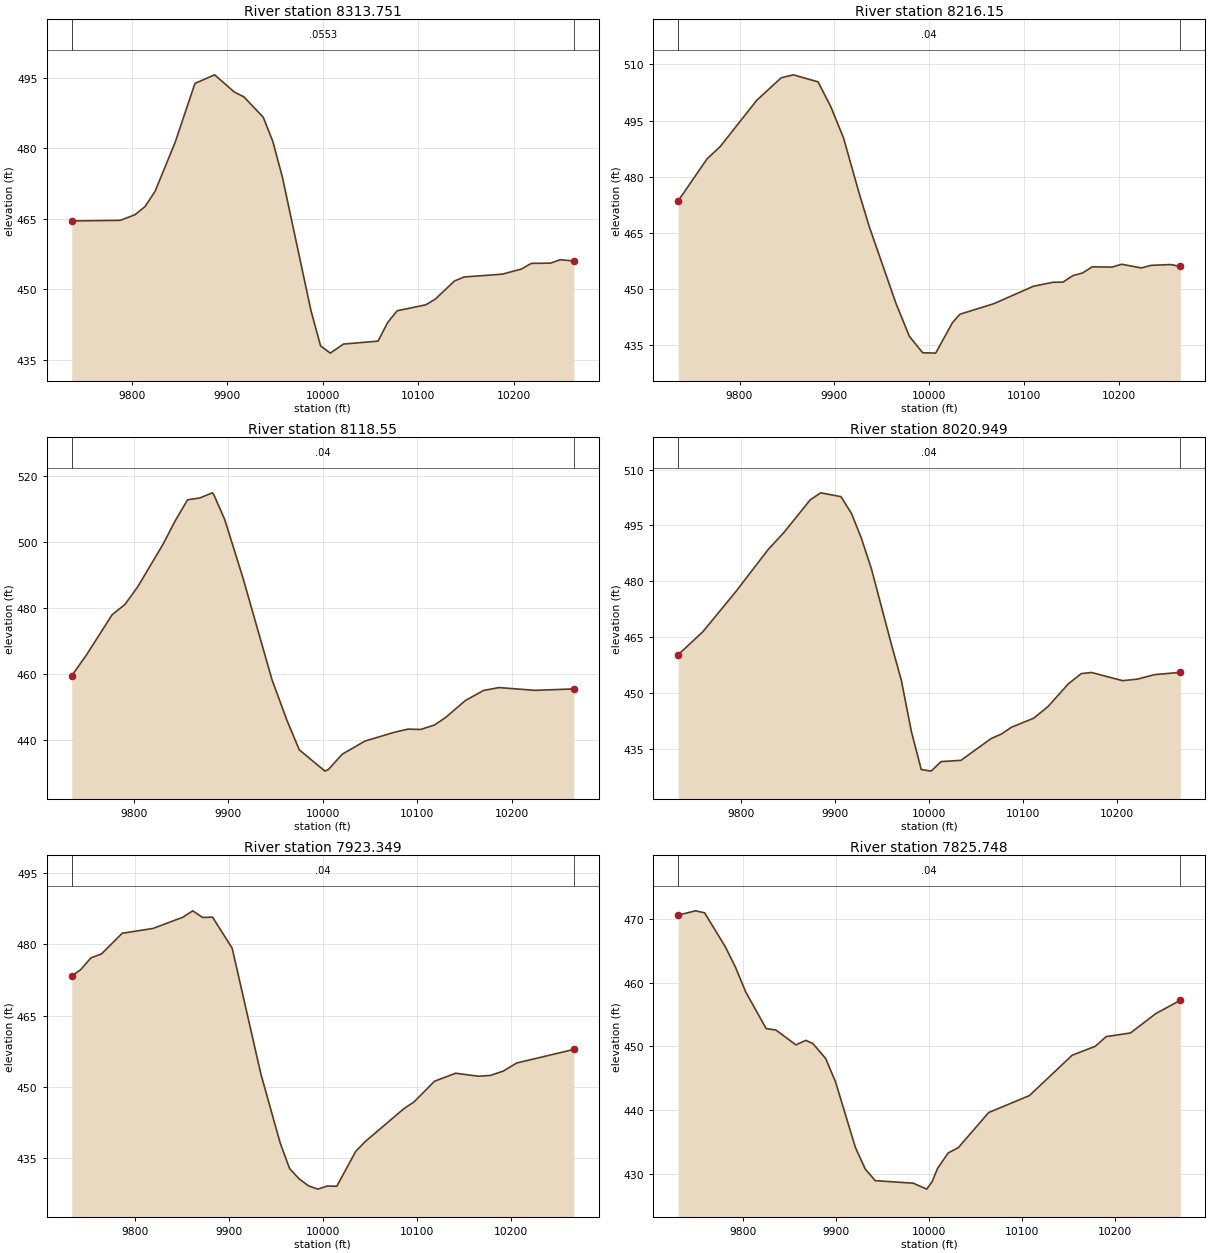
Type RM Length L Ch R = 1 ,8313.751,97.600600,97.600600,97.600600
XS GIS Cut Line= 6
789422.744995081780202.117023924789530.188020231 780164.46746158
789609.688303561 780146.38485701789718.599897452780147.850433894
789854.106891586780137.945480163789939.028189592780125.149813809
#Sta/Elev= 30
 9736.77464.5644 9787.66464.68929803.099 465.8899813.622467.62429824.144470.8627
 9845.19481.28439865.959493.81949886.631495.64239907.111492.00319917.285490.9536
9937.555486.62359947.579 481.4899957.604473.91929987.684445.42029997.713437.9873
 10007.8436.445310021.79438.375910057.95438.997510067.98442.9294   10078445.4604
10108.08446.722210118.11447.954910138.16451.797210148.19452.640710188.36453.2455
10208.53454.347310218.62455.540310238.85455.582810249.02456.313310263.28456.0469
#Mann= 3 , 0 , 0
 9736.77  0.0553       0 9736.77  0.0553       010263.28  0.0553       0
#XS Ineff= 2 , 0
       0                               0
Bank Sta=9736.77,10263.28
Exp/Cntr=0.3,0.1

Type RM Length L Ch R = 1 , 8216.15,97.600500,97.600500,97.600500
XS GIS Cut Line= 6
789540.533866068780384.046779664789648.985138779 780296.59141554
789748.678138615780202.738212299789779.093658363780179.464552241
789821.930652667780161.624498281789984.584236279780119.392765606
#Sta/Elev= 30
9735.392473.55829765.735484.73859779.669488.05969818.208500.4207  9843.9506.4284
9856.747507.21299882.774505.32389896.175498.69669909.577490.37059925.779475.8058
9936.604 466.7269964.943446.06279978.974437.33739993.006432.941810006.72432.8337
10024.41440.988310032.22443.222810067.71446.018110109.93450.723610130.55451.7824
10140.85451.798910151.16453.526510161.46454.249110171.77455.906310192.38455.8252
10202.69456.587110223.43455.602110233.81 456.29610254.58456.503710264.53455.9902
#Mann= 3 , 0 , 0
9735.392    0.04       09735.392    0.04       010264.53    0.04       0
#XS Ineff= 2 , 0
       0                               0
Bank Sta=9735.392,10264.53
Exp/Cntr=0.3,0.1

Type RM Length L Ch R = 1 , 8118.55,97.600600,97.600600,97.600600
XS GIS Cut Line= 6
789625.524760798 780486.68423113789783.169675309780305.648058232
 789863.15234069780224.846903384 789927.58118235780173.604266187
789957.923711243780155.089399362790011.503079146780127.883920603
#Sta/Elev= 30
9734.069459.37679749.828 465.7539776.802477.85799790.289 480.9519803.776486.2576
9830.406499.06119843.551506.27899856.695512.6972 9869.84513.26539882.985514.8166
9884.521514.2765 9896.13 506.6979915.336489.08999946.151458.17639961.853445.9676
9975.028436.930510002.29430.453910006.19431.025310020.59435.592210044.67439.5728
10076.48 442.28410090.31443.192910103.56443.080210118.14444.417410129.93446.6841
10150.93451.844510170.26454.908810186.78455.780110224.96454.9382 10265.9 455.378
#Mann= 3 , 0 , 0
9734.069    0.04       09734.069    0.04       0 10265.9    0.04       0
#XS Ineff= 2 , 0
       0                               0
Bank Sta=9734.069,10265.9
Exp/Cntr=0.3,0.1

Type RM Length L Ch R = 1 ,8020.949,97.600600,97.600600,97.600600
XS GIS Cut Line= 6
789768.963365395780577.368306659789842.425063654780445.460420408
789899.502164174780289.537064742789923.735941678780239.033329592
789974.918031634780176.519815403790040.204017537780130.472464805
#Sta/Elev= 30
9732.807460.22539759.083  466.419794.324477.24849828.321488.43479845.521 493.143
 9873.21501.82559884.413503.73039906.014502.69789917.201 498.1789927.614491.5882
9938.415483.29539959.733462.91519970.289453.28439980.845439.68049991.402429.3664
10001.94428.922610012.52431.481510033.67431.817210065.87437.687710076.77438.8953
10087.57440.737110110.97443.1291 10126.1 446.22310148.12452.417610161.81455.1441
 10172.6455.436310205.69453.239610221.81453.664610239.86454.863710267.13455.4701
#Mann= 3 , 0 , 0
9732.807    0.04       09732.807    0.04       010267.13    0.04       0
#XS Ineff= 2 , 0
       0                               0
Bank Sta=9732.807,10267.13
Exp/Cntr=0.3,0.1

Type RM Length L Ch R = 1 ,7923.349,97.600500,97.600500,97.600500
XS GIS Cut Line= 6
789901.583974089780603.159560383789963.220066951780451.749038446
789984.906770784780300.134896982790000.575290299780246.401245315
 790044.01039942 780178.37174291790104.827371709780126.610101173
#Sta/Elev= 30
9732.849473.33099742.017474.61559753.253477.15499764.489477.97979786.512482.3271
9819.258483.34049851.052485.70329861.592487.05119872.132485.65599882.672485.7242
9903.532 479.192 9934.17452.65079954.596438.22169964.703432.77199974.745430.6531
9984.787429.16469994.829428.472110004.86429.126410014.89429.078810035.02436.4127
10045.12438.485810086.34445.413710096.96 446.80910118.87451.181410141.33452.8684
10165.69452.232110178.45452.412810192.01453.311810206.44455.029810267.14457.8739
#Mann= 3 , 0 , 0
9732.849    0.04       09732.849    0.04       010267.14    0.04       0
#XS Ineff= 2 , 0
       0                               0
Bank Sta=9732.849,10267.14
Exp/Cntr=0.3,0.1

Type RM Length L Ch R = 1 ,7825.748,97.600600,97.600600,97.600600
XS GIS Cut Line= 6
789966.363130599780620.050345707790006.427961777780538.024386589
790056.635692892780402.722280866790127.386455134 780257.54553779
790170.641723931780193.860040992790216.515689318780146.888156469
#Sta/Elev= 30
9729.963470.57259748.432471.25019758.303470.94349780.545 465.6279791.562462.4023
9802.579458.52029824.508452.78119835.174452.54539856.507450.22379867.173450.9298
9874.666450.45049888.506448.09629899.172444.42019920.505434.14569931.171430.7368
9941.837428.92699982.817428.52269997.316427.5929 10003.1428.773710008.86430.8179
10020.31433.264110031.26434.103210063.92439.606510107.78 442.27310153.73448.6002
10178.57 449.99810190.35  451.5210216.45452.090210243.75455.136610270.06457.2136
#Mann= 3 , 0 , 0
9729.963    0.04       09729.963    0.04       010270.06    0.04       0
#XS Ineff= 2 , 0
       09918.083                       0
Bank Sta=9729.963,10270.06
Exp/Cntr=0.3,0.1

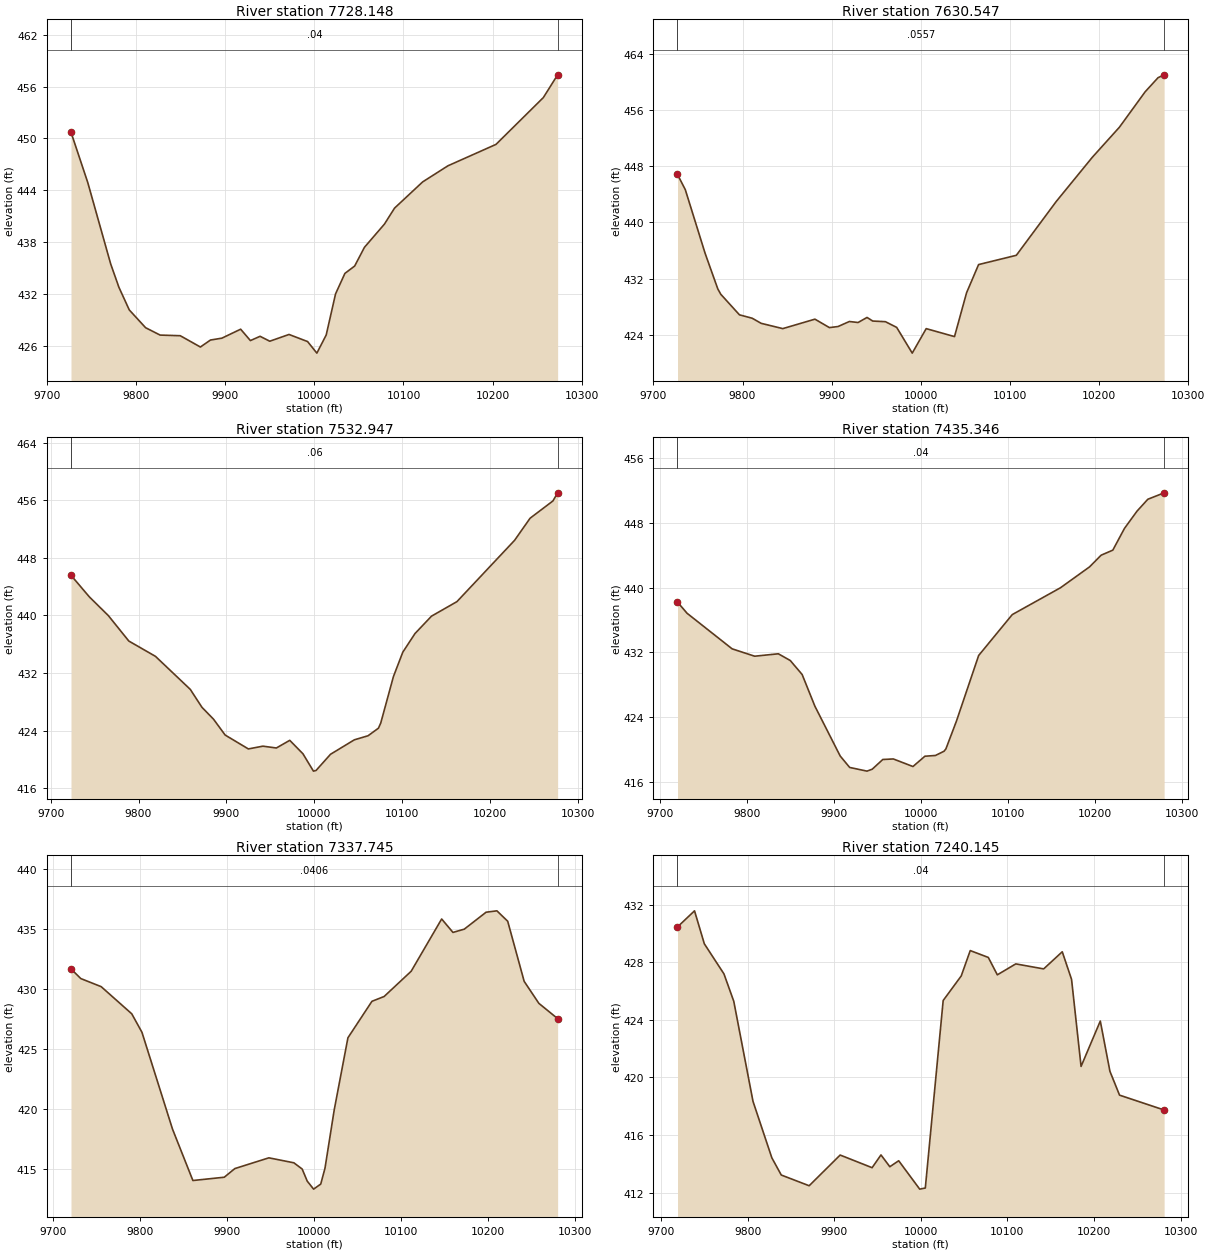
Type RM Length L Ch R = 1 ,7728.148,97.600600,97.600600,97.600600
XS GIS Cut Line= 6
790042.243356468  780641.2000118790136.040415835780472.623181213
790173.864253635780364.971905025790201.009080596780309.979325973
790252.878125287780236.684557564790313.368467403780173.764727653
#Sta/Elev= 30
9727.084450.7083 9745.93444.86989771.621435.44949780.829432.75489792.463430.1317
9810.764 428.0759827.058 427.221 9849.64427.14699872.221  425.849883.512426.6475
9896.287 426.8639917.384427.90129928.327426.58329939.162427.08049949.997426.5099
9971.653427.2928 9992.46426.469310002.85425.131910013.33427.232910023.82431.9901
 10034.3434.362110045.26435.216210056.22437.382110078.61440.064810089.99441.9201
 10121.5444.953910149.82446.816110203.77449.298610256.86454.7151 10272.9457.3518
#Mann= 3 , 0 , 0
9727.084    0.04       09727.084    0.04       0 10272.9    0.04       0
#XS Ineff= 2 , 0
       09915.647                       0
Bank Sta=9727.084,10272.9
Exp/Cntr=0.3,0.1

Type RM Length L Ch R = 1 ,7630.547,97.600500,97.600500,97.600500
XS GIS Cut Line= 6
790067.392480803780672.205890464790156.229551946780543.540875984
790191.274460639780499.525087464790213.752889137780477.258766659
790289.468302141780412.673041654790432.875662844780270.288837979
#Sta/Elev= 30
9727.065446.82919735.821444.66699758.054435.60349772.277 430.5429775.654429.7766
9796.582426.85239810.854426.37059820.886425.6449 9845.19424.89199881.255426.2372
  9897.5425.03549907.119425.18769919.901425.90379929.609425.76029939.682426.4809
9946.112425.96879960.322425.87799972.949425.06539990.398421.403710006.06  424.89
10037.81423.756710051.32429.981910064.83434.005310107.18435.325410151.96442.9881
10192.53449.291110222.76453.543610251.69458.593310266.16460.601210272.97 461.008
#Mann= 3 , 0 , 0
9727.065  0.0557       09727.065  0.0557       010272.97  0.0557       0
#XS Ineff= 2 , 0
       09945.226                       0
Bank Sta=9727.065,10272.97
Exp/Cntr=0.3,0.1

Type RM Length L Ch R = 1 ,7532.947,97.600600,97.600600,97.600600
XS GIS Cut Line= 6
790121.039682362780736.630148524790180.940096453780669.937454068
790282.667332463780551.974278066790344.423749875780484.178366936
790423.560034435780401.621234842790497.779096302 780331.32623603
#Sta/Elev= 30
 9723.14445.57539744.032442.57459765.655439.97469788.929436.44579819.304434.3154
9858.918429.72749872.123427.24799885.328425.59259898.533423.39469924.942421.4657
9941.499421.84999956.812421.59669972.046 422.6599987.022420.7967    9999418.3842
10001.97418.476410018.42420.723110045.57422.731810061.09423.292110072.97424.3457
10075.54425.0463   10090431.509210100.68434.899910114.53437.482710133.35439.9005
10162.25441.913110227.88 450.42910245.47453.4921 10271.5 455.89610276.84457.0219
#Mann= 3 , 0 , 0
 9723.14    0.06       0 9723.14    0.06       010276.84    0.06       0
#XS Ineff= 2 , 0
       09967.277                       0
Bank Sta=9723.14,10276.84
Exp/Cntr=0.3,0.1

Type RM Length L Ch R = 1 ,7435.346,97.600600,97.600600,97.600600
XS GIS Cut Line= 6
790186.473897337 780788.38751449 790309.44527014780681.467218741
790346.017526936780638.713580224790441.015460045780507.226111804
790499.090882953 780446.69308775790568.965940445780384.230340356
#Sta/Elev= 30
9720.386438.22249731.421436.83629783.192432.43869809.078 431.5299836.249431.8277
9849.944430.99929863.616429.26839878.252425.35379907.351419.18519918.252417.7723
9938.119417.31569944.185417.55549956.305418.75389968.425418.82149990.979417.8855
10004.72419.159210016.79419.250610026.74419.779310028.85420.069610040.91423.4889
10066.47 431.616 10105.1436.676210160.53 439.99610193.83442.569810207.24 444.023
10220.65444.646510234.06 447.33810248.46449.470210260.89450.939510279.62451.7356
#Mann= 3 , 0 , 0
9720.386    0.04       09720.386    0.04       010279.62    0.04       0
#XS Ineff= 2 , 0
       0                               0
Bank Sta=9720.386,10279.62
Exp/Cntr=0.3,0.1

Type RM Length L Ch R = 1 ,7337.745,97.600500,97.600500,97.600500
XS GIS Cut Line= 6
790235.377155891780807.557164997790404.372357206780701.289127125
790435.692344704780673.162678903790484.094353222780616.205539933
790526.439374832780574.599169584790671.212791155780462.209259234
#Sta/Elev= 30
9720.385431.66829731.654430.85989755.075430.18429790.207427.91789801.917426.3772
9837.049 418.289 9860.47413.99719896.516414.27219908.678414.99369947.801415.8913
  9976.5415.47749986.063414.95559991.893413.9437 9999.21413.2783 10007.4413.7005
10012.28415.022910022.86419.881810038.64425.915310066.23428.960310080.25 429.363
10111.33431.471610146.37435.835910159.36434.713610172.34434.985610197.43436.4008
10209.85436.516710222.26435.646310241.18430.628810258.06428.792210279.64427.5164
#Mann= 3 , 0 , 0
9720.385  0.0406       09720.385  0.0406       010279.64  0.0406       0
#XS Ineff= 2 , 0
       09877.822                       0
Bank Sta=9720.385,10279.64
Exp/Cntr=0.3,0.1

Type RM Length L Ch R = 1 ,7240.145,97.600600,97.600600,97.600600
XS GIS Cut Line= 6
790247.641513615780820.455732814790315.298104746780784.505670273
790373.581043994780759.521761321 790601.27520226 780699.11977674
 790678.35222909780668.981679034790771.394361186780624.165894703
#Sta/Elev= 30
9719.097430.45049738.754431.56939750.078429.28089772.726427.1912 9784.05425.2935
9806.267418.33929828.027414.41929838.907413.2261 9871.11 412.482 9906.88414.6132
9943.776413.7352 9954.01414.62189964.243413.80329974.477414.21649998.718412.2469
 10005.2412.322910025.82 425.34210046.66427.048410057.08428.809110077.92428.3331
10088.34427.124910109.62427.884610141.83427.5371 10163.3428.726910174.04426.8082
10185.02420.765910207.22423.916210218.32420.431210229.42418.773110280.91417.7404
#Mann= 3 , 0 , 0
9719.097    0.04       09719.097    0.04       010280.91    0.04       0
#XS Ineff= 2 , 0
       0 9887.95                       0
Bank Sta=9719.097,10280.91
Exp/Cntr=0.3,0.1