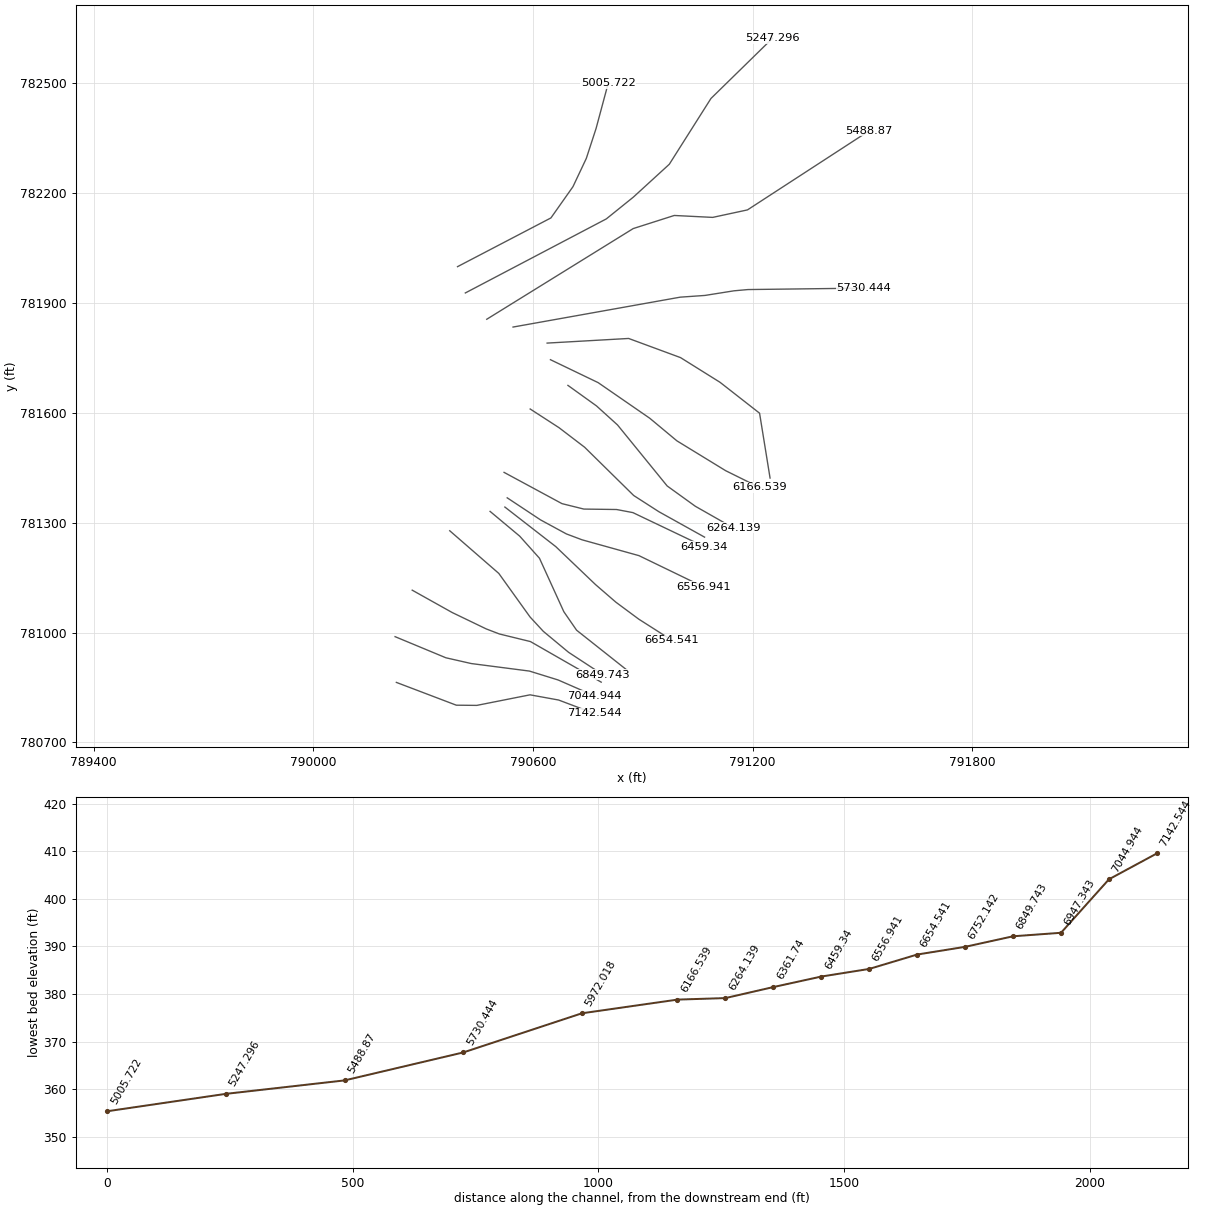
HEC-RAS study 17510_ras.prj: 17510

--- 17510_ras.g01 (geometry) --- (continued)

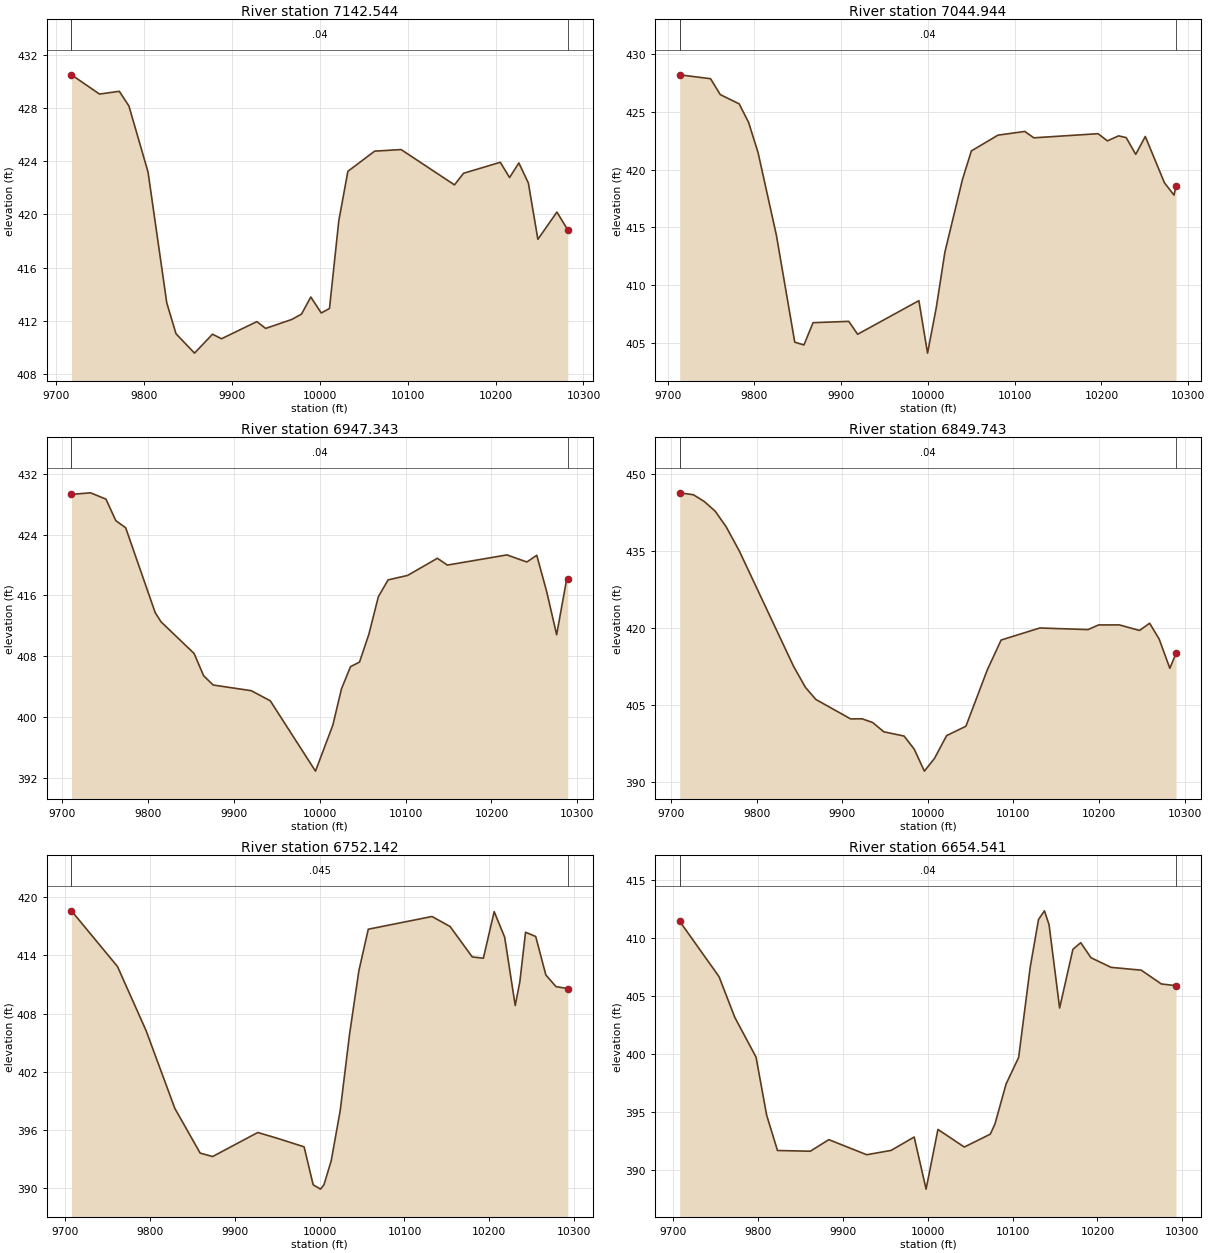
Type RM Length L Ch R = 1 ,7142.544,97.600600,97.600600,97.600600
XS GIS Cut Line= 6
790226.680013947780863.950780419790390.433202268780801.703281175
790446.339816674780801.135543444790591.827845073780829.999645701
790669.820429413780815.817687586790766.405311375780779.339928946
#Sta/Elev= 30
9717.865430.52279749.726429.07359772.227429.28019783.155 428.1789804.906423.1994
9826.206413.33639836.726411.00799857.765409.54829878.212 410.9769888.414410.6305
9928.623411.92229938.637411.41059968.452412.0888 9979.41412.49179989.984413.7764
10001.83412.574610011.19  412.9110021.79419.520610032.12  423.2510062.57424.7705
10092.63424.890910153.33422.228110163.61423.102710205.41423.930310215.96422.7813
10226.51 423.88310237.31422.371110248.14418.1264 10269.8420.179410282.16418.8295
#Mann= 3 , 0 , 0
9717.865    0.04       09717.865    0.04       010282.16    0.04       0
#XS Ineff= 2 , 0
       09936.063                       0
Bank Sta=9717.865,10282.16
Exp/Cntr=0.3,0.1

Type RM Length L Ch R = 1 ,7044.944,97.600600,97.600600,97.600600
XS GIS Cut Line= 6
790223.159481942780988.880767188790361.916334894780931.204071247
790431.277577964780915.435164461790590.242449911780894.861850655
790668.547385062780870.575318231 790767.14724635780827.528814933
#Sta/Elev= 30
9713.976428.2043 9749.55427.86739760.721426.49259782.516425.68899793.413424.0788
9804.244421.48299825.407414.31979846.571405.06129857.152404.81849867.658406.7477
9908.849406.86249919.042405.74569989.622408.65469999.626404.112110009.64408.0351
10019.65 412.86810039.91419.159210050.13421.6164 10080.8422.9823 10111.7423.3036
10122.09422.751310196.15423.108710206.94422.485910219.81422.921610228.56422.7679
10239.58421.321810250.59422.868510272.63418.862510283.65 417.79410286.01 418.548
#Mann= 3 , 0 , 0
9713.976    0.04       09713.976    0.04       010286.01    0.04       0
#XS Ineff= 2 , 0
       09967.747                       0
Bank Sta=9713.976,10286.01
Exp/Cntr=0.3,0.1

Type RM Length L Ch R = 1 ,6947.343,97.600500,97.600500,97.600500
XS GIS Cut Line= 6
790269.969471443781115.849713387790379.020665474781054.883186363
790472.116390835781010.045360078790508.293154161780996.164179604
 790592.91041567780975.456802682790786.223879901780864.612960788
#Sta/Elev= 30
 9711.24429.28129733.474429.48849751.374428.6581 9762.83425.82739774.287424.8963
9808.657413.73349815.445412.51989853.913408.35849865.012 405.4289876.112404.2068
9920.509403.45899942.596402.12869995.181392.877710015.36398.922310025.46403.7139
10035.91406.613810046.42407.224210057.32410.885210068.32 415.81510079.68418.0352
10102.41418.622510137.05420.877610148.64419.9832   10218421.320810241.13 420.389
10252.69421.274910264.25416.489410275.82410.821210287.38418.0593 10288.8418.1661
#Mann= 3 , 0 , 0
 9711.24    0.04       0 9711.24    0.04       0 10288.8    0.04       0
#XS Ineff= 2 , 0
       09948.211                       0
Bank Sta=9711.24,10288.8
Exp/Cntr=0.3,0.1

Type RM Length L Ch R = 1 ,6849.743,97.600600,97.600600,97.600600
XS GIS Cut Line= 6
790372.494426368781278.137249766790506.459324442781161.656858845
790591.844246989781042.611040727790628.037023413781003.449030374
790697.066319365780946.130972143790791.138206283  780884.5388749
#Sta/Elev= 30
9709.929446.27619725.881445.90669738.638444.58769751.394442.7092 9764.15439.6923
9779.409435.03039843.073412.50819856.947408.41879869.052406.08579909.722402.2978
9922.951402.32459935.518401.59629948.467399.79429972.216398.96059984.068396.4074
9995.919392.140910007.75394.620510021.91399.048110044.46400.870810069.36411.7959
10085.64 417.64410130.83419.984410187.25419.671610199.42420.576210223.76420.5875
 10247.4419.504510259.21420.910210270.39417.819210282.82412.150810290.07415.0467
#Mann= 3 , 0 , 0
9709.929    0.04       09709.929    0.04       010290.07    0.04       0
#XS Ineff= 2 , 0
       09941.787                       0
Bank Sta=9709.929,10290.07
Exp/Cntr=0.3,0.1

Type RM Length L Ch R = 1 ,6752.142,97.600600,97.600600,97.600600
XS GIS Cut Line= 6
790482.681857721781331.010235114790563.623748637781263.361047761
790617.569409831781203.079600454790684.100384272781057.065996559
790718.961544054781006.510259304790856.591098949780897.508291759
#Sta/Elev= 30
9707.417418.60059761.684412.85999795.498406.2355 9829.26398.24669859.149393.6353
9873.813393.28379927.059395.76019949.598395.1774 9981.68 394.2859992.367390.3734
   10001389.925910005.08390.374910013.66392.8526 10024.3398.042510035.22405.8502
10046.21412.400410057.35416.704910132.49418.016410153.76416.985710179.95413.8515
10193.04413.716810205.78418.517510218.18415.873710230.59408.840410236.03411.2829
10242.76416.393410254.74415.957110266.72  411.9910278.69410.791210292.58410.5867
#Mann= 3 , 0 , 0
9707.417   0.045       09707.417   0.045       010292.58   0.045       0
#XS Ineff= 2 , 0
       09958.401                       0
Bank Sta=9707.417,10292.58
Exp/Cntr=0.3,0.1

Type RM Length L Ch R = 1 ,6654.541,97.600500,97.600500,97.600500
XS GIS Cut Line= 6
790523.094011706781342.887016188790662.039990197781234.868898946
790770.764745396781131.023914741790826.180109439781083.115457845
790888.682790925781036.771380133790979.594719907780978.859092731
#Sta/Elev= 30
9707.354 411.4639753.731406.67679772.316403.15799797.347399.72439809.863 394.707
9822.637391.64819861.377 391.5869883.174392.58719927.826391.28279956.567391.6553
9983.828392.81319997.871 388.30910011.85393.467310042.97391.949710073.55393.0584
10079.01393.920410092.23397.403810107.01399.692110120.64 407.48210130.44411.6132
10137.43412.367910142.89411.169510155.34403.9652   10171409.039110180.24409.6139
10192.31408.314210216.02407.481110251.59407.238110275.31406.045510292.61 405.899
#Mann= 3 , 0 , 0
9707.354    0.04       09707.354    0.04       010292.61    0.04       0
#XS Ineff= 2 , 0
       09955.708        10022.81       0
Bank Sta=9707.354,10292.61
Exp/Cntr=0.3,0.1

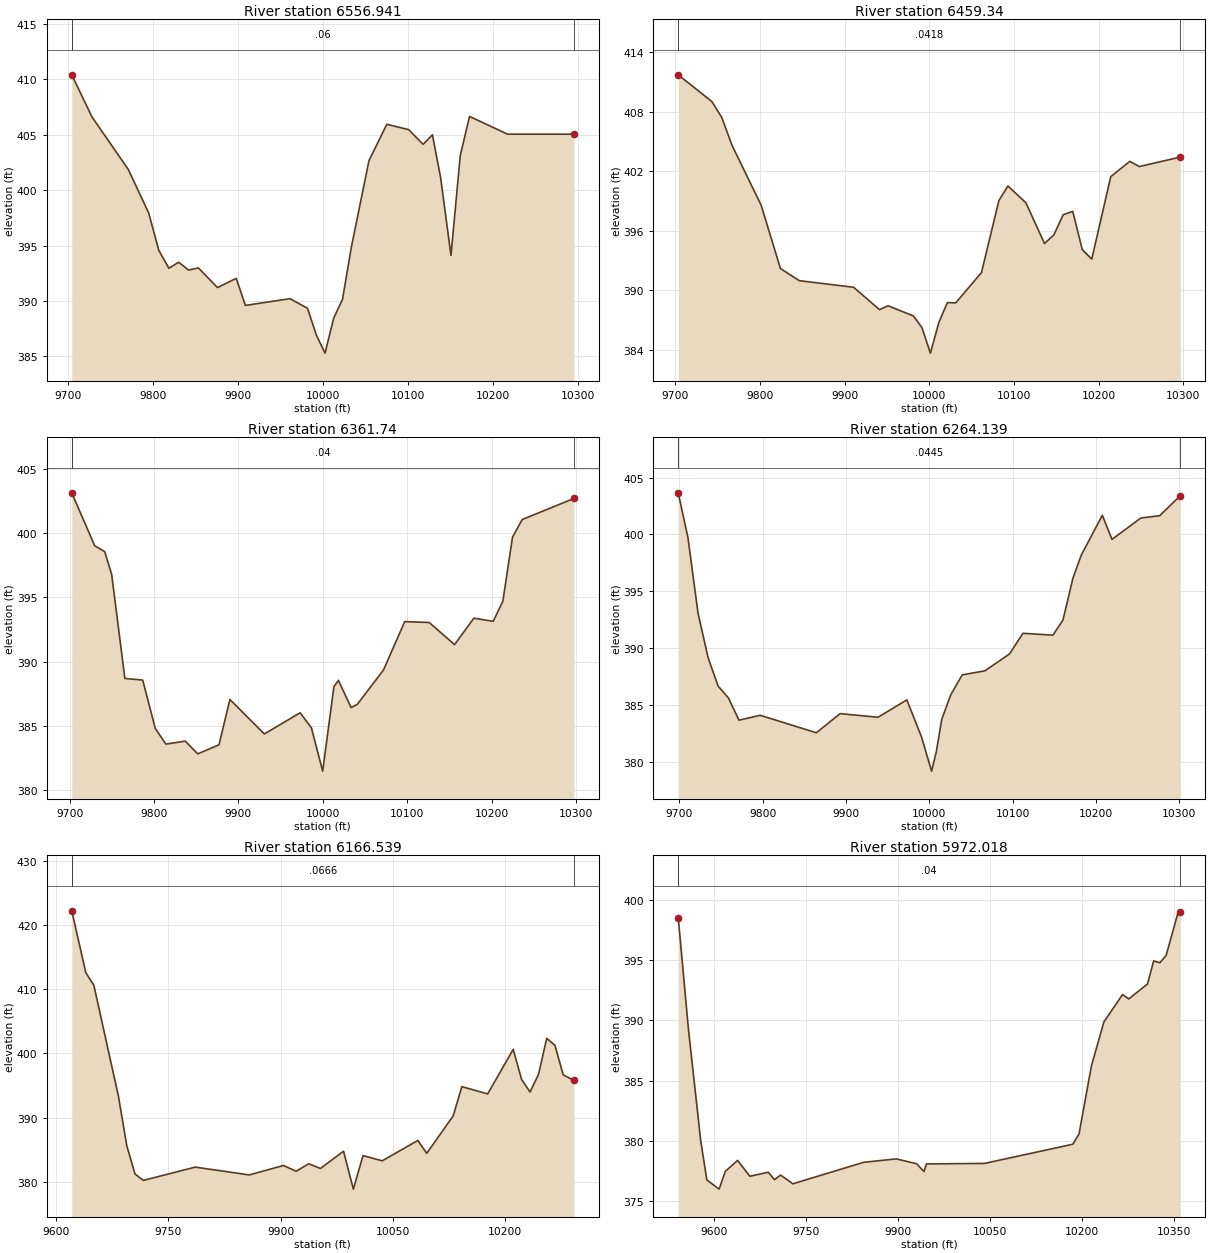
Type RM Length L Ch R = 1 ,6556.941,97.600600,97.600600,97.600600
XS GIS Cut Line= 6
790529.450452961781368.094013488790620.592286117781307.782951618
790691.117404218781269.490521528790733.946709009781253.399177352
790889.350616074 781210.15900094791064.410904457 781125.41226468
#Sta/Elev= 30
9704.343410.40529728.071406.61879770.954401.85839794.936397.93849806.927394.5449
9818.733392.94849830.303 393.4919841.874392.78279853.444392.98169875.955391.2025
9898.077392.0374 9908.76389.59289961.377390.20119981.986389.33449992.291386.9453
 10002.6385.286910012.91388.456310023.21390.135210033.52394.796910054.35402.6536
10075.43405.9405 10101.1405.4583 10118.2  404.1310129.12 404.99310138.77401.1284
10150.97394.107610161.89403.108210172.81406.651310217.71 405.04710295.67 405.047
#Mann= 3 , 0 , 0
9704.343    0.06       09704.343    0.06       010295.67    0.06       0
#XS Ineff= 2 , 0
       09955.225                       0
Bank Sta=9704.343,10295.67
Exp/Cntr=0.3,0.1

Type RM Length L Ch R = 1 , 6459.34,97.600600,97.600600,97.600600
XS GIS Cut Line= 6
 790520.89621826781437.600098717790679.088610139781352.198603237
790738.843839294781337.374050151790828.139283288 781336.17648998
790872.727506194781327.702210336791068.129281291781234.479945085
#Sta/Elev= 30
9703.352411.7177 9743.06409.03199754.703407.43829767.002404.59799801.276398.5958
9824.121392.20749846.487390.98079910.558390.31999941.167388.06219951.254 388.456
9981.315387.4258 9991.32386.263610001.33383.683410011.33386.767210021.33388.7669
10031.33388.748510061.68 391.79910082.34399.064710092.98400.522710114.26398.8198
10136.14394.726210147.09395.575110158.32397.627310169.55 397.96410180.79394.1109
10192.02393.155210214.49401.467810236.97402.9983 10248.2402.476110296.66 403.433
#Mann= 3 , 0 , 0
9703.352  0.0418       09703.352  0.0418       010296.66  0.0418       0
#XS Ineff= 2 , 0
       09974.761                       0
Bank Sta=9703.352,10296.66
Exp/Cntr=0.3,0.1

Type RM Length L Ch R = 1 , 6361.74,97.600500,97.600500,97.600500
XS GIS Cut Line= 6
790592.210179946781610.704619216 790670.92264404781559.697045757
790741.058599287781506.135444888790874.891773301781374.468913961
 790943.76565026781330.130307195791068.499300181781260.725350034
#Sta/Elev= 30
9702.602403.14149729.759399.02189741.675398.56149749.869 396.7949765.507388.6935
9786.646 388.5639801.527384.8008 9814.11383.58049837.088 383.8139851.858382.8197
9877.023383.5246 9889.99387.05399930.755384.36949973.189386.01859986.541384.8406
9999.846381.476510013.19388.055410018.52 388.54210033.52386.426710040.89386.6733
10071.92389.353210097.08393.114110126.06393.047710156.09391.323710178.98393.3831
10201.87393.138510213.31394.694410224.75399.6865 10236.2401.059410297.42402.7009
#Mann= 3 , 0 , 0
9702.602    0.04       09702.602    0.04       010297.42    0.04       0
#XS Ineff= 2 , 0
       09963.829                       0
Bank Sta=9702.602,10297.42
Exp/Cntr=0.3,0.1

Type RM Length L Ch R = 1 ,6264.139,97.600600,97.600600,97.600600
XS GIS Cut Line= 6
790695.328151948781675.202869891790773.389278257781619.090973855
790830.773724151781567.114548237 790966.33148741781400.536547611
791043.250608795781345.041323456791146.650030613781286.249447754
#Sta/Elev= 30
9698.567403.66759710.248399.71489722.325393.07579734.402389.16069746.479386.6481
9758.869385.60379771.508383.64839796.923384.08089864.384382.5442 9892.96384.2258
9938.515383.90559973.045385.4368 9990.72382.169310002.77379.163410008.51380.8856
10014.99383.725910025.93 385.89910039.56387.638310066.68387.989810096.44 389.483
10112.47391.299910148.49391.132810160.53392.464810172.56396.164910182.57398.1878
10207.79401.692810219.42399.566910253.95401.447110276.76401.656110301.45403.4148
#Mann= 3 , 0 , 0
9698.567  0.0445       09698.567  0.0445       010301.45  0.0445       0
#XS Ineff= 2 , 0
       09891.034                       0
Bank Sta=9698.567,10301.45
Exp/Cntr=0.3,0.1

Type RM Length L Ch R = 1 ,6166.539,194.520800,194.520800,194.520800
XS GIS Cut Line= 6
790647.534611927781745.394601992790777.952888572781682.653702855
790918.942323325781585.342234551790992.897353121 781523.76792881
791126.149934429781442.198726492791217.863776887 781396.79181611
#Sta/Elev= 30
9620.794422.19929639.565 412.5779650.312410.6044 9683.23393.29049694.317385.6083
9705.403381.1876 9716.49380.20259785.852382.27089858.044381.05569903.779382.5255
9920.731381.62579937.636382.79289953.223382.05839984.109 384.7519997.231378.8422
10010.17384.063710035.84383.252110083.45386.424510095.35384.416510130.75390.2565
10142.26394.8112 10176.8393.6746 10210.9400.615610222.18395.916410233.47393.9685
10244.75396.717610255.78402.3385 10266.8401.229110277.82396.6419   10292 395.789
#Mann= 3 , 0 , 0
9620.794  0.0666       09620.794  0.0666       0   10292  0.0666       0
#XS Ineff= 2 , 0
       0 9859.67                       0
Bank Sta=9620.794,10292
Exp/Cntr=0.3,0.1

Type RM Length L Ch R = 1 ,5972.018,241.574000,241.574000,241.574000
XS GIS Cut Line= 6
790638.478585064781790.727639601790861.136452705781803.378654808
791002.827822953781751.087791964791110.783152699781683.615710855
791218.738482445781599.275609523791247.414116919781422.161396638
#Sta/Elev= 30
9542.406398.54019558.955389.29579578.987380.00959589.003376.73279609.035 375.971
9619.051377.44999639.084378.35739659.116377.04199689.164377.3749 9699.18376.7591
9709.196377.13899729.229376.41419844.156378.19819897.453378.4845 9930.81378.0789
9942.602377.4303 9946.81378.067310041.15 378.10810185.09379.702510195.22 380.556
10215.48386.231310235.74389.869710266.13392.149310276.26 391.78310306.65393.0192
10316.78394.936810326.91394.790110337.04395.3996 10357.3399.106510360.18 398.986
#Mann= 3 , 0 , 0
9542.406    0.04       09542.406    0.04       010360.18    0.04       0
#XS Ineff= 2 , 0
       09778.103        10020.44       0
Bank Sta=9542.406,10360.18
Exp/Cntr=0.3,0.1

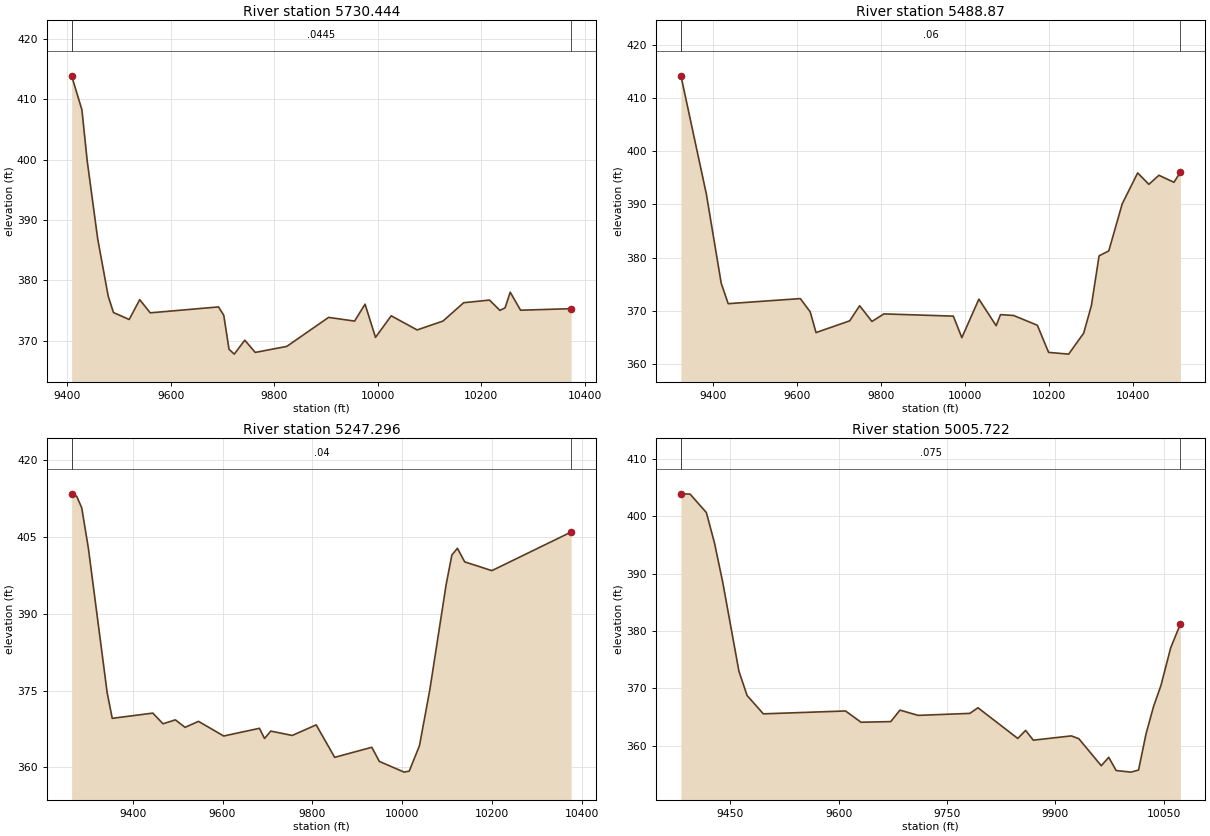
Type RM Length L Ch R = 1 ,5730.444,241.573900,241.573900,241.573900
XS GIS Cut Line= 6
 790545.41300413781834.547283441791001.941738039781916.174000651
791069.616276354  781920.8998916791148.837591439781933.520506635
791186.826203406781936.937352031791502.800123185781940.890434325
#Sta/Elev= 30
9408.075413.90199427.972408.25979438.131399.83359458.448 386.8799478.765377.3612
9488.924374.64689519.399373.48749539.717376.77539560.034374.59239692.095375.5724
9702.254374.19479712.413 368.5569722.571367.74469742.888370.05489763.206368.0293
9824.157369.02529904.982373.83829955.254 373.2239975.497376.0297 9995.74370.5245
10026.09374.103510076.22 371.75610126.23373.229210166.23376.272710216.23376.7064
10236.23375.003610246.23375.411310256.24378.017710276.24375.028610374.04375.2835
#Mann= 3 , 0 , 0
9408.075  0.0445       09408.075  0.0445       010374.04  0.0445       0
#XS Ineff= 2 , 0
       09745.166        10045.88       0
Bank Sta=9408.075,10374.04
Exp/Cntr=0.3,0.1

Type RM Length L Ch R = 1 , 5488.87,241.574000,241.574000,241.574000
XS GIS Cut Line= 6
790473.581283927781855.830756068790873.644683659782103.536048949
790985.716041446 782139.31357339791090.698745817782134.068430498
791185.687965274782154.513874367 791517.95049575 782370.47591503
#Sta/Elev= 30
9323.731414.17549384.207 391.9479419.492375.21369436.128371.35419607.679 372.312
9631.202369.82749645.084365.92539725.295368.13389748.819370.96799778.056368.0172
9806.565369.43359971.692369.01329991.952364.9676 10032.5372.211710073.51367.2147
10083.87369.293110114.94 369.13710171.59367.300110198.32362.201410246.03361.8726
10281.69365.803510300.04 370.97210318.39380.343410341.44381.274210373.44390.1119
10410.14395.929510436.85393.784910460.71 395.48510496.49394.168210511.93396.0879
#Mann= 3 , 0 , 0
9323.731    0.06       09323.731    0.06       010511.93    0.06       0
#XS Ineff= 2 , 0
       09808.498        10047.75       0
Bank Sta=9323.731,10511.93
Exp/Cntr=0.3,0.1

Type RM Length L Ch R = 1 ,5247.296,241.574000,241.574000,241.574000
XS GIS Cut Line= 6
790415.051734209781927.662476212790800.131060034782129.931580871
790874.168149114782189.562559485790972.195727348782279.207277775
791085.960532248782458.852152854791253.861977875  782623.1354215
#Sta/Elev= 30
9264.194413.46849275.431412.98889286.727 410.7089301.478402.80569343.205374.6127
  9354.5369.56879444.865370.59079467.456 368.5059495.018369.27149516.523367.8109
9546.526368.97319602.541366.11199682.073367.62019693.368365.62199707.244367.0721
9755.071366.22119808.347368.28819849.481361.94249931.982363.90659948.845361.1489
10003.99359.050110015.37359.246110038.13 364.21410061.17375.149810097.55395.7443
10110.22401.505710122.56402.816510138.86400.162210199.26398.448510375.63405.9958
#Mann= 3 , 0 , 0
9264.194    0.04       09264.194    0.04       010375.63    0.04       0
#XS Ineff= 2 , 0
       09917.958                       0
Bank Sta=9264.194,10375.63
Exp/Cntr=0.3,0.1

Type RM Length L Ch R = 1 ,5005.722,241.574000,241.574000,241.574000
XS GIS Cut Line= 6
790393.768261582781999.494196385790648.874668449782132.625478536
790709.060156912782217.952161789790745.495545179782295.125677034
790772.139331996782376.821800813790805.463547736782500.798523977
#Sta/Elev= 30
9381.408403.90079394.077403.85099416.637400.64139427.917395.32179439.197388.5653
9461.756372.98629473.036368.76029495.596 365.5549609.453 366.0559630.954364.0906
9672.166 364.205 9684.81366.20299710.099365.28899781.655365.63559792.935366.6149
9848.076361.26999858.967362.66839869.601360.96769922.261361.7108 9932.71361.2221
9963.809 356.5139974.121357.97729984.433 355.67510005.07355.397410015.43355.7569
10025.78362.052610036.14366.8069 10046.5370.512310059.96377.058510073.47381.2361
#Mann= 3 , 0 , 0
9381.408   0.075       09381.408   0.075       010073.47   0.075       0
#XS Ineff= 2 , 0
       09908.482                       0
Bank Sta=9381.408,10073.47
Exp/Cntr=0.3,0.1