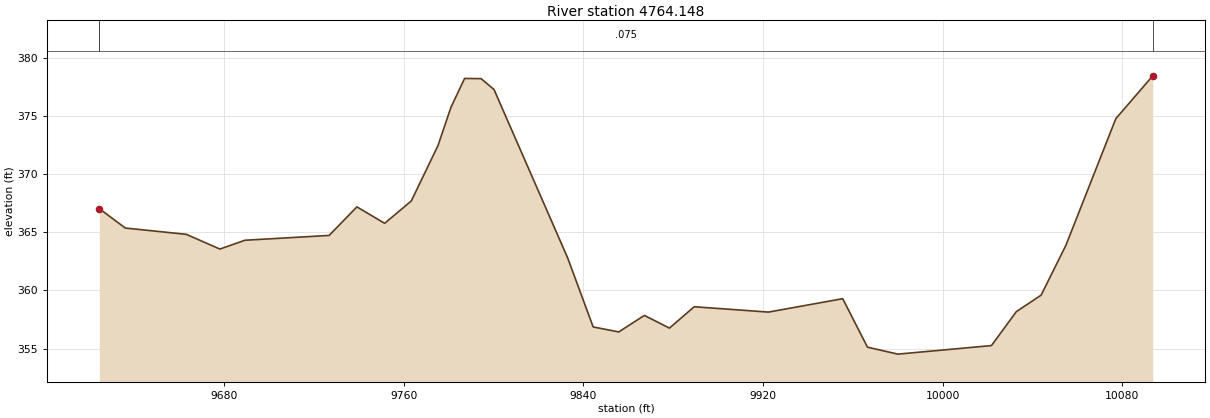
HEC-RAS study 17510_ras.prj: 17510

--- 17510_ras.g01 (geometry) --- (continued)

Type RM Length L Ch R = 1 ,4764.148,0.000000,0.000000,0.000000
XS GIS Cut Line= 6
790359.067527413782176.463037059790408.519108593782232.964868113
 790439.10368982782274.998787627790462.240789473782311.200750321
790499.435085028782379.239772677790594.124862552782579.604754344
#Sta/Elev= 30
9624.361367.02089635.942 365.3589663.074364.8182 9678.09363.55159689.198364.3087
9726.728364.72329739.095367.17519751.462365.7635 9763.33367.68579775.198 372.432
9780.979375.72329787.066378.20669794.425378.19149800.177377.25419832.945362.8077
9844.341356.86349855.738356.43379867.135357.85229878.318356.76299889.345358.5973
9922.425358.13769955.505 359.2899966.532355.12359980.099354.527210021.76 355.262
10032.82358.173910043.88359.593710054.94363.883810077.14 374.749 10093.6378.4334
#Mann= 3 , 0 , 0
9624.361   0.075       09624.361   0.075       0 10093.6   0.075       0
#XS Ineff= 2 , 0
       09935.943                       0
Bank Sta=9624.361,10093.6
Exp/Cntr=0.3,0.1